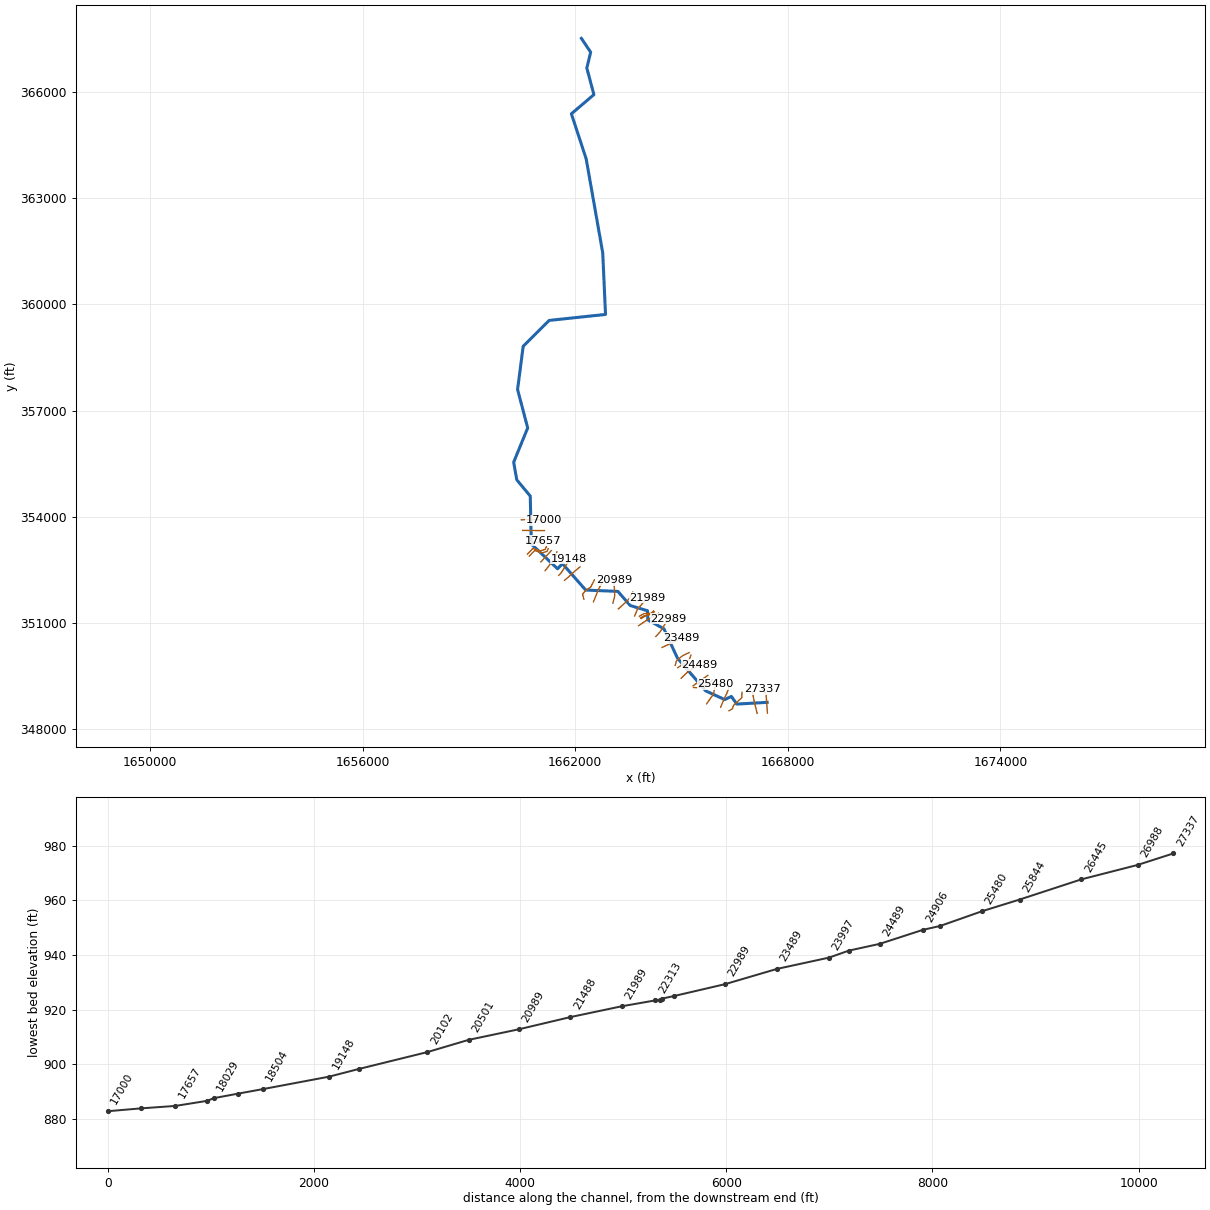
--- ARCHESFK.prj (project) ---

Proj Title=ARCHESFK
Current Plan=p01
Default Exp/Contr=0,0
English Units
Geom File=g01
Flow File=f01
Plan File=p01
BEGIN DESCRIPTION:
---------- MODELED AS PART OF WVEMD CTP PROGRAM, 2023----------
Stream Name: Arches Fork
Flood Zone:  AFH
Wetzel County, WV
HEC-RAS Version: RAS 6.3
Vertical Datum: NAVD88
Projection: NAD 1983 StatePlane West Virginia S FIPS 4702 (US Feet)
Terrain: 1-meter West Virginia FEMA R3 South Central (collected 2018-2020)
Land Use: 2019 NLCD
Hydrologic Method:
WV 2010 Regional Regression Equations
Additional Model Notes:
None
END DESCRIPTION:
DSS File=dss
DSS Export Rating Curves= 0
DSS Export Rating Curve Sorted= 0
DSS Export Volume Flow Curves= 0
DXF OffsetX= 0
DXF OffsetY= 0
DXF ScaleX= 0
DXF ScaleY= 0

--- ARCHESFK.p01 (plan) ---

Plan Title=Floodplain
Program Version=6.30
Short Identifier=Floodplain
Geom File=g01
Flow File=f01
Subcritical Flow
K Sum by GR= 0
Std Step Tol= 0.01
Critical Tol= 0.01
Num of Std Step Trials= 20
Max Error Tol= 0.3
Flow Tol Ratio= 0.001
Split Flow NTrial= 30
Split Flow Tol= 0.02
Split Flow Ratio= 0.02
Log Output Level= 0
Friction Slope Method= 1
Unsteady Friction Slope Method= 2
Unsteady Bridges Friction Slope Method= 1
Parabolic Critical Depth
Global Vel Dist= 0 , 0 , 0
Global Log Level= 0
CheckData=True
Encroach Param=-1 ,0,0, 0
Computation Interval=0.1SEC
Output Interval=1SEC
Instantaneous Interval=Max Profile
Mapping Interval=1HOUR
Computation Time Step Use Courant=        0
Computation Time Step Use Time Series=    0
Computation Time Step Count To Double=0
Computation Time Step Max Doubling=0
Computation Time Step Max Halving=0
Computation Time Step Residence Courant=0
Run HTab= 0
Run UNet= 0
Run Sediment= 0
Run PostProcess= 0
Run WQNet= 0
Run RASMapper=-1
UNET Theta= 0
UNET Theta Warmup= 0
UNET ZTol= 0
UNET ZSATol= 0
UNET MxIter= 0
UNET Max Iter WO Improvement= 0
UNET MaxInSteps= 0
UNET DtIC= 0
UNET DtMin= 0
UNET MaxCRTS= 0
UNET WFStab= 0
UNET SFStab= 0
UNET WFX= 1
UNET SFX= 1
UNET Gravity=32.17405
UNET 1D Methodology=Finite Difference
UNET DSS MLevel= 1
UNET Pardiso=0
UNET DZMax Abort= 0
UNET Use Existing IB Tables= 0
UNET Froude Reduction=False
UNET Froude Limit= 0
UNET Froude Power= 0
UNET D1 Cores= 0
UNET WindReference=Eulerian
UNET WindDragFormulation=Hsu (1988)
UNET D2 Coriolis=0
UNET D2 Cores= 0
UNET D2 Theta= 1
UNET D2 Theta Warmup= 1
UNET D2 Z Tol= 0.01
UNET D2 Volume Tol= 0.01
UNET D2 Max Iterations= 20
UNET D2 Equation= 0
UNET D2 RampUpFraction=0.1
UNET D2 TimeSlices= 1
UNET D2 Turbulence Formulation=Non-Conservative (original)
UNET D2 Eddy Viscosity=0.3
UNET D2 Transverse Eddy Viscosity=0.1
UNET D2 Smagorinsky Mixing=0
UNET D2 BCVolumeCheck=0
UNET D2 Cores=0
UNET D2 SolverType=PARDISO (Direct)
UNET D2 Minimum Iterations= 3
UNET D2 Maximum Iterations= 30
UNET D2 Restart Number= 10
UNET D2 Relaxation Coeff=1.3
UNET D2 SOR Precondition Iterations= 10
UNET D2 ILUT Maximum Fill= 8
UNET D2 ILUT Tolerance=1E-08
UNET D2 Convergence Tolerance=0.00001
UNET D1D2 MaxIter= 0
UNET D1D2 ZTol=0.01
UNET D1D2 QTol=0.1
UNET D1D2 MinQTol=1
DSS File=dss
Write IC File= 0
Write IC File at Fixed DateTime=0
Write IC File at Sim End=0
Echo Input=False
Echo Parameters=False
Echo Output=False
Write Detailed= 0
HDF Write Warmup=0
HDF Write Time Slices=0
HDF Flush=0
HDF Compression= 1
HDF Chunk Size= 1
HDF Spatial Parts= 1
HDF Use Max Rows=0
HDF Fixed Rows= 1
Calibration Method= 0
Calibration Iterations= 20
Calibration Max Change=0.05
Calibration Tolerance=0.2
Calibration Maximum=1.5
Calibration Minimum=0.5
Calibration Optimization Method= 1
WQ AD Non Conservative
WQ ULTIMATE=-1
WQ Max Comp Step=1HOUR
WQ Output Interval=15MIN
WQ Output Selected Increments= 0
WQ Output face flow=0
WQ Output face velocity=0
WQ Output face area=0
WQ Output face dispersion=0
WQ Output cell volume=0
WQ Output cell surface area=0
WQ Output cell continuity=0
WQ Output cumulative cell continuity=0
WQ Output face conc=0
WQ Output face dconc_dx=0
WQ Output face courant=0
WQ Output face peclet=0
WQ Output face adv mass=0
WQ Output face disp mass=0
WQ Output cell mass=0
WQ Output cell source sink temp=0
WQ Output nsm pathways=0
WQ Output nsm derived pathways=0
WQ Create Restart=0
WQ Fixed Restart=0
WQ System Summary=0
WQ Write To DSS=0
Sorting and Armoring Iterations= 10
XS Update Threshold= 0.02
Bed Roughness Predictor= 0
Hydraulics Update Threshold= 0.02
Energy Slope Method= 1
Volume Change Method= 1
Sediment Retention Method= 0
Sediment TS Multiplier= 1
Warm Up Method= 0
XS Weighting Method= 0
Number of US Weighted Cross Sections= 1
Number of DS Weighted Cross Sections= 1
Upstream XS Weight=0
Main XS Weight=1
Downstream XS Weight=0
Number of DS XS's Weighted with US Boundary= 1
Upstream Boundary Weight= 1
Weight of XSs Associated with US Boundary= 0
Number of US XS's Weighted with DS Boundary= 1
Downstream Boundary Weight= 0.5
Weight of XSs Associated with DS Boundary= 0.5
Percentile Method= 0
Sediment Output Level= 3
Mass or Volume Output= 0
Output Increment Type= 1
Profile and TS Output Increment= 1
Transport Output Increment 1
XS Output Flag= 0
XS Output Increment= 10
Read HDF5 Sediment Hotstart= 0
Sediment Hotstart Type= 0
Write Gradation File= 0
Read Gradation Hotstart= 0
Write HDF5 File= 1
Write Binary Output= 1
Write DSS Sediment File= 0
DSS Sediment Output Type= 1
SV Curve= 0
Specific Gage Flag= 0
Subcell Erosion Methods= 0
Subcell Deposition Methods= 0
Advection Scheme= 1
Matrix Solver= 0
Implicit Weighting Factor= 1
Maximum Outer Loop Convergence Iterations= 5
Convergence Maximum Absolute= 0.001
Convergence RMSE= 0.0001
Grain Fractions Max Abs Error= 0.001
Max Subgrid Regions= 1
Max Subgrid Length Scale= 3.402823E+38
Initial Layer Thickness= 3.402823E+38
Min Layer Thickness= 3.402823E+38
Max Layer Thickness= 3.402823E+38
Number of Layers= 5

--- ARCHESFK.f01 (steady flow) ---

Flow Title=Flow
Program Version=6.31
Number of Profiles= 1
Profile Names=F01pct
River Rch & RM=ARCHESFK,Main,27337
     640
River Rch & RM=ARCHESFK,Main,25844
     775
River Rch & RM=ARCHESFK,Main,25075
    1020
River Rch & RM=ARCHESFK,Main,22989
    1190
River Rch & RM=ARCHESFK,Main,20102
    1440
River Rch & RM=ARCHESFK,Main,18262
    1890
River Rch & RM=ARCHESFK,Main,12501
    2330
River Rch & RM=ARCHESFK,Main,8039
    2610
Boundary for River Rch & Prof#=ARCHESFK,Main            , 1
Up Type= 0
Dn Type= 3
Dn Slope=0.00297
DSS Import GetInterval= 0
DSS Import GetPeak= 0
DSS Import FillOption= 0

--- ARCHESFK.g01 (geometry) ---

Geom Title=Geometry
Program Version=6.30

River Reach=ARCHESFK        ,Main
Reach XY= 30
     1667415.772      348761.055      1666558.27      348712.316
      1666406.48      348928.201     1666218.916      348839.263
     1665683.552      349084.463     1664885.599      350008.866
     1664503.515      350837.624     1664049.636      351089.034
      1664039.45      351347.649     1663552.281      351495.216
     1663204.233      351894.192     1662295.427      351931.871
      1661640.87      352675.876       1661501.7      352532.396
     1660760.349      353232.903     1660732.129      354584.356
     1660351.161      355044.821     1660263.254      355542.217
     1660659.515      356508.466     1660374.219      357594.584
     1660532.116      358816.425     1661265.574       359545.58
     1662855.089      359714.426     1662777.119       361450.74
     1662309.685      364106.134     1661892.238      365379.467
     1662527.872      365920.461     1662328.269      366670.695
     1662435.642      367120.836 1662173.5625154367510.270537142

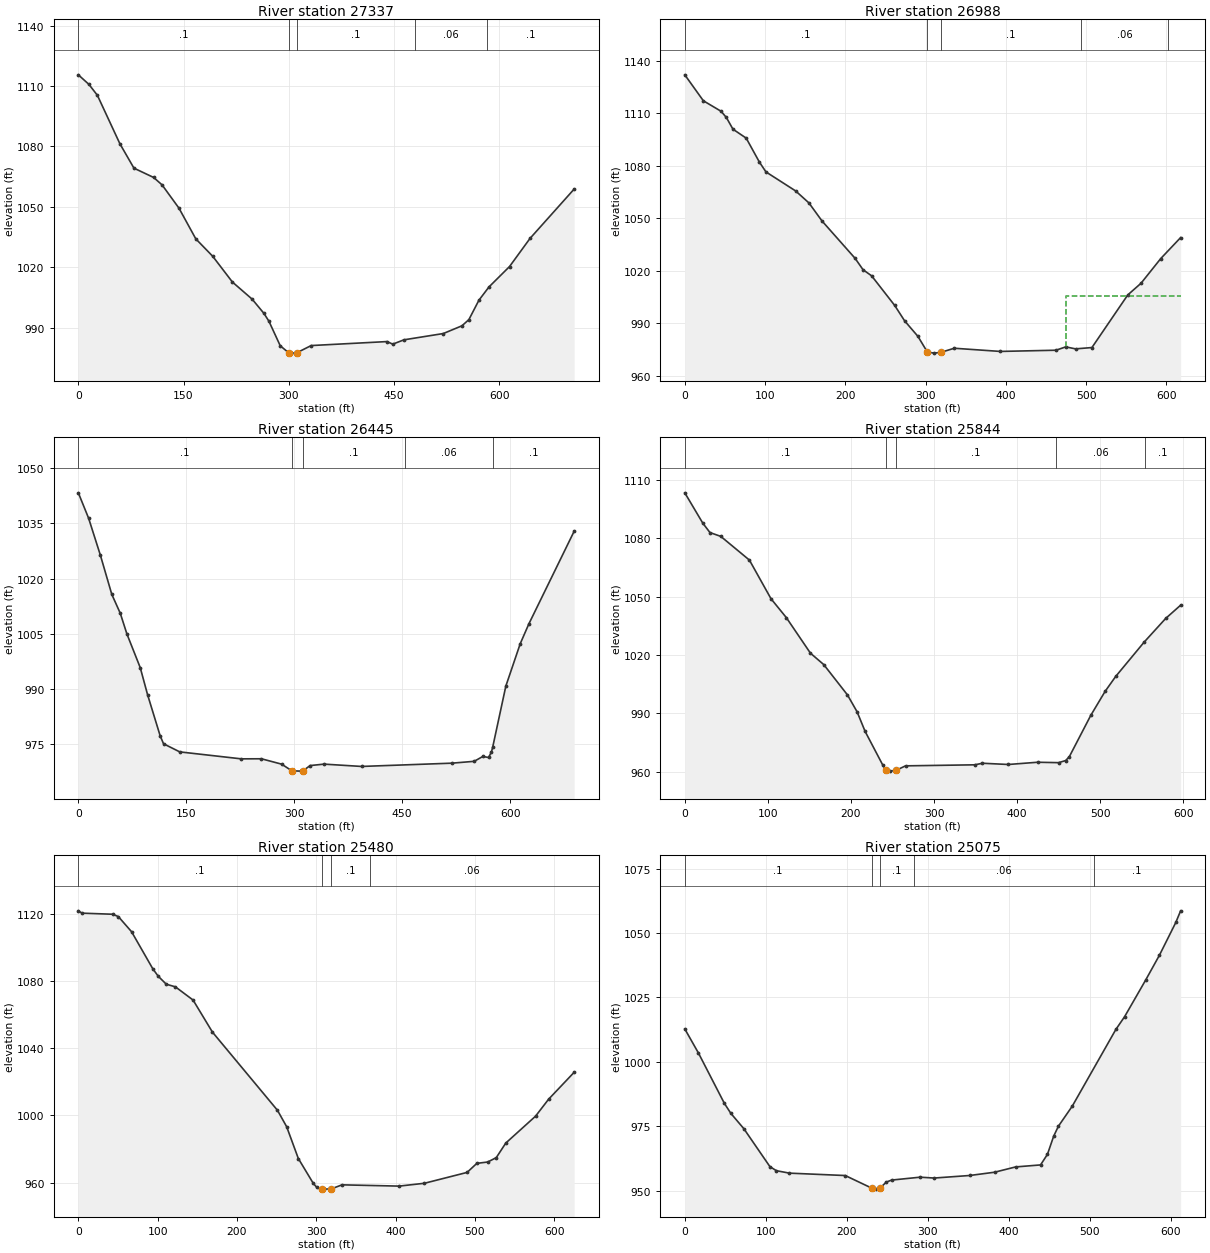
Type RM Length L Ch R = 1 ,27337   ,347.2,348.1,350.4
XS GIS Cut Line= 3
1667423.75474825348457.4088047681667386.01029833348988.734522891
1667287.29404469349132.453774514
#Sta/Elev= 30
       0 1115.56    15.2 1110.78    27.2 1105.36    59.3 1081.28    79.3 1069.19
   107.4 1064.56   119.4 1060.88   143.5 1049.31   167.5 1034.06   191.6 1025.41
   219.7  1012.6   247.8 1004.11   264.7  997.01   271.8  993.11   287.9  980.94
   299.9  977.47   303.9  977.28   311.6 977.465     332  981.04   440.2  983.02
   448.3  981.74   464.3  983.89   520.4  987.01     547  990.86   556.9  993.94
   571.2 1003.57   585.5 1010.15   614.9 1020.32     644 1034.25     707  1058.8
#Mann= 5 ,-1,0
       0      .1       0   299.9    .045       0   311.6      .1       0
     480     .06       0  582.66      .1       0
Bank Sta=299.9,311.6
XS Rating Curve= 0 ,0
Exp/Cntr(USF)=0,0
Exp/Cntr=0.3,0.1

Type RM Length L Ch R = 1 ,26988   ,553,543.9,537
XS GIS Cut Line= 6
1667132.88902725348450.061600253 1667111.6892665348541.385564595
 1667073.8980035348699.4298679231667049.58177917348796.787612841
1667034.38102217348871.669680923 1666999.8312225349053.056129172
#Sta/Elev= 30
       0 1132.08    23.1 1117.26    45.1 1111.28    51.8  1107.7      60 1101.01
    76.5  1095.9    92.9 1082.24   101.1  1076.6   138.1 1065.72   154.6  1058.9
     171 1048.53   212.2 1027.19   222.1 1020.68   232.7 1017.24   261.5 1000.29
   273.9  991.46   290.4  982.64   302.3973.5767     311  973.04   319.2   973.5
   335.7  975.83   393.1  974.01   462.4   974.7   474.6  976.61   486.8  975.47
   507.2  976.23   551.9 1006.32   568.3 1012.94     593 1027.11   617.7 1039.07
#Mann= 5 ,-1,0
       0      .1       0   302.3    .045       0   319.2      .1       0
  493.01     .06       0  602.31      .1       0
#XS Ineff= 2 , 0
                             475         1005.61
Permanent Ineff=
       F       F
Bank Sta=302.3,319.2
XS Rating Curve= 0 ,0
Exp/Cntr(USF)=0,0
Exp/Cntr=0.3,0.1

Type RM Length L Ch R = 1 ,26445   ,590.8,600.6,598.5
XS GIS Cut Line= 5
1666337.61346954348523.4616887891666440.26821136348582.726282003
1666459.31754489348665.2733939811666700.60910298348894.923692689
1666706.95888083349047.318360956
#Sta/Elev= 30
       0 1043.27    14.3 1036.37    30.6 1026.37    46.5 1015.72    58.3 1010.58
    67.5 1004.98      86  995.85    96.3  988.44   113.7  977.35   118.4  975.19
   140.9  972.99   226.4   971.1   254.4  971.12   282.5  969.66   296.7  967.85
   309.3  967.77     312967.8525   322.1  969.28   341.4  969.67   393.6  969.04
   519.1  969.93     550  970.43     562  971.75     570  971.47     574  972.97
   575.9  974.44     594  990.85     614 1002.35     626 1007.73   688.9 1032.85
#Mann= 5 ,-1,0
       0      .1       0   296.7    .045       0     312      .1       0
  453.25     .06       0  576.36      .1       0
Bank Sta=296.7,312
XS Rating Curve= 0 ,0
Exp/Cntr(USF)=0,0
Exp/Cntr=0.3,0.1

Type RM Length L Ch R = 1 ,25844   ,363.3,364.2,361.1
XS GIS Cut Line= 5
1666104.94866353348624.4522915211666186.94903119348825.505610462
1666265.29332151348987.3469430061666297.91826037349068.545368889
1666338.41545999349173.407035807
#Sta/Elev= 30
       0  1103.3    21.7  1087.7    30.3 1082.89    43.3 1080.93    77.8 1068.74
   103.8 1048.88   122.2 1039.22   151.3 1020.91   167.3 1015.06   195.8   999.5
   207.4  990.83   217.1  980.72   238.3  963.49   242.7  960.67   247.2  960.34
   254.2  960.71   265.7  963.05     349  963.58   358.3  964.39   389.4  963.75
   424.6   964.9     450  964.69   458.5  965.77   462.9  967.75   488.7  988.95
   505.9 1001.25   518.7 1008.96     553 1026.62   578.9 1038.77   596.9 1045.58
#Mann= 5 ,-1,0
       0      .1       0   242.7    .045       0   254.2      .1       0
  446.94     .06       0  554.45      .1       0
Bank Sta=242.7,254.2
XS Rating Curve= 0 ,0
Exp/Cntr(USF)=0,0
Exp/Cntr=0.3,0.1

Type RM Length L Ch R = 1 ,25480   ,408.3,404.6,401.1
XS GIS Cut Line= 6
 1665710.2629355348720.5836970061665812.31653717348870.710693344
1665858.65437101348929.6872814151665906.56733292349018.474505425
1665941.06726393349185.4115075021665964.73388326349279.808300346
#Sta/Elev= 30
       0 1122.03     4.7 1120.63    43.1    1120    50.4 1118.62    67.1 1109.59
    93.9 1087.46   100.8 1082.99   110.9 1078.27   122.4  1076.7   144.7 1068.81
   169.1  1049.7   251.1 1003.07   262.7  993.26   277.4  974.32   296.1  959.62
   300.7  957.05     307  956.21   309.8  956.06   318.9   956.2   332.5  958.62
   404.4  957.86   436.4  959.55   490.2  966.03   502.5  971.43   516.2  972.23
     527  974.85     539  983.54   576.5  999.56     593 1009.69   625.2 1025.74
#Mann= 4 ,-1,0
       0      .1       0     307    .045       0   318.9      .1       0
  367.44     .06       0
Bank Sta=307,318.9
XS Rating Curve= 0 ,0
Exp/Cntr(USF)=0,0
Exp/Cntr=0.3,0.1

Type RM Length L Ch R = 1 ,25075   ,165.6,169.6,169.3
XS GIS Cut Line= 5
1665335.38934653349182.2957006841665477.67140563349170.536852823
1665627.00877346349238.7381704121665695.21009105349238.738170412
1665871.59280895349397.482616524
#Sta/Elev= 30
       0  1012.8    16.8 1003.49    48.9  983.92    56.9  980.05      73  974.08
   105.1  959.41   113.1  957.82   129.2  956.87   198.2  955.94   230.6   951.1
   236.7  950.67   241.2951.1104   248.8  953.38   255.4  954.18   290.6   955.3
     308  954.97     352  955.96   382.7  957.23   408.6  959.28   439.4  960.06
   447.9  964.16   455.6   971.2   461.5   975.1   478.6  982.87   532.4  1012.6
   543.2 1017.55   569.2 1031.75   586.2 1041.38   606.5 1054.14   612.4 1058.61
#Mann= 5 ,-1,0
       0      .1       0   230.6    .045       0   241.2      .1       0
  282.77     .06       0  505.14      .1       0
Bank Sta=230.6,241.2
XS Rating Curve= 0 ,0
Exp/Cntr(USF)=0,0
Exp/Cntr=0.3,0.1

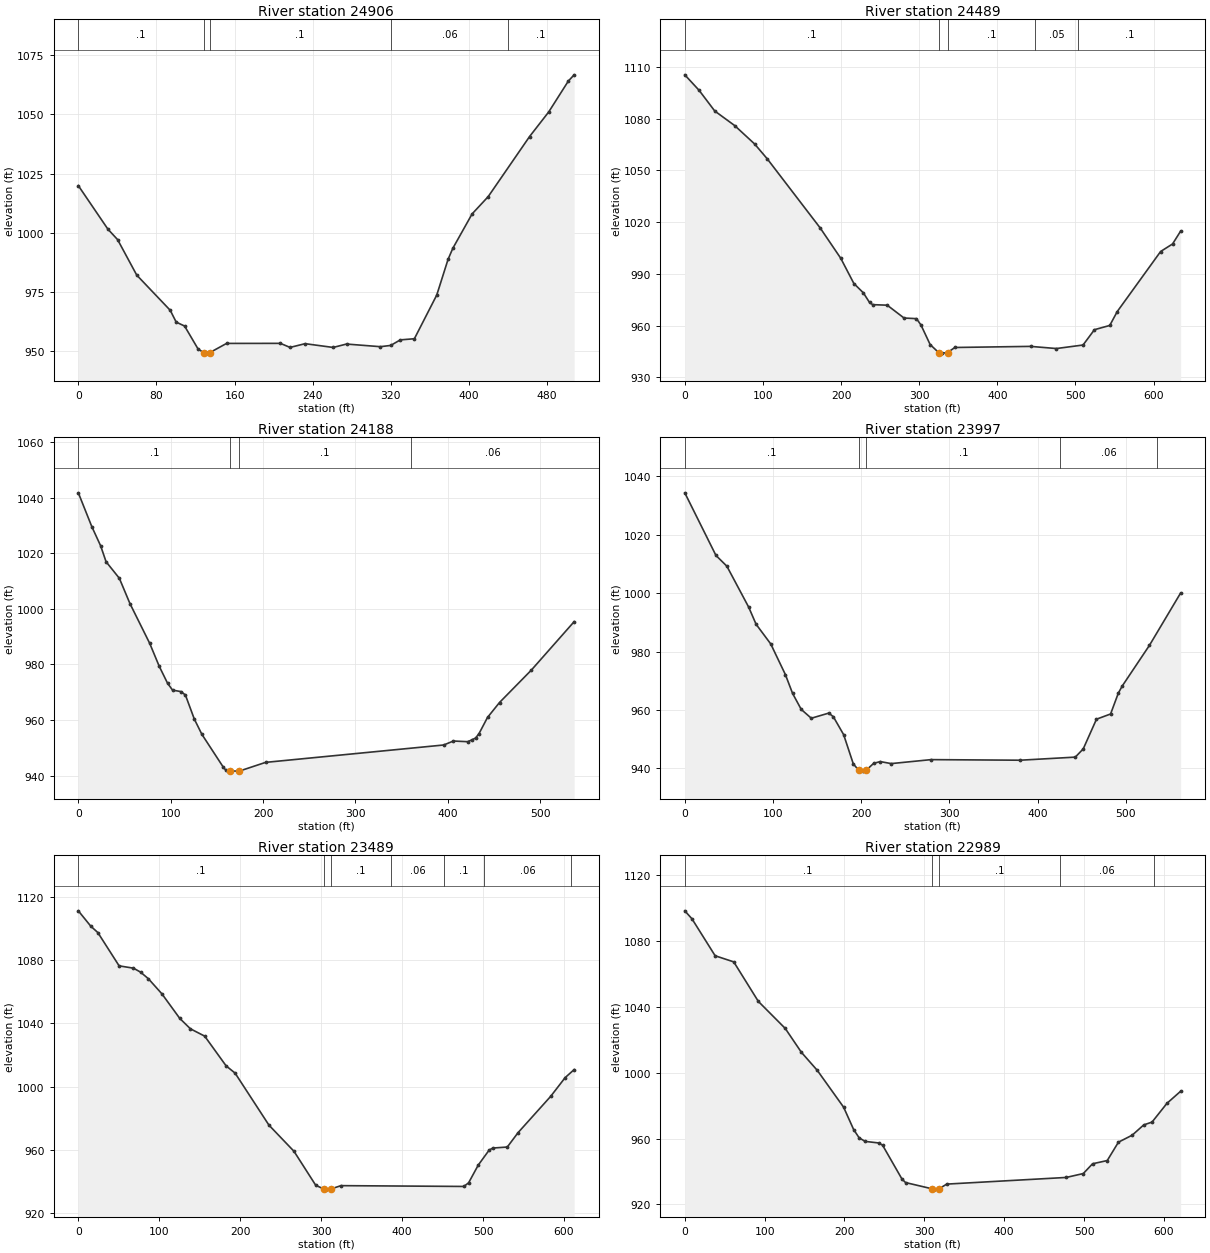
Type RM Length L Ch R = 1 ,24906   ,416.6,416.7,415.5
XS GIS Cut Line= 2
1665327.37059852349229.5623032131665741.37667316349523.488693863
#Sta/Elev= 30
       0 1019.89    30.3 1001.52    40.2  997.12    59.8  982.14    94.1  967.29
   100.2  962.31   108.8  960.65   122.6  950.97   128.5  949.39   131.8  949.22
   134.4949.3867   151.8  953.32   206.9  953.34   216.8  951.63   232.2  953.21
   260.9  951.62   274.6  953.05   309.2  951.94   319.8  952.46   329.7  954.81
   344.1  955.29     367  973.72   378.6  988.81   383.5  993.48   403.2 1007.96
   419.7 1015.27     462 1040.58   481.7 1051.02   501.8 1064.06   507.7 1066.65
#Mann= 5 ,-1,0
       0      .1       0   128.5    .045       0   134.4      .1       0
     320     .06       0     440      .1       0
Bank Sta=128.5,134.4
XS Rating Curve= 0 ,0
Exp/Cntr(USF)=0,0
Exp/Cntr=0.3,0.1

Type RM Length L Ch R = 1 ,24489   ,300.6,301.5,301
XS GIS Cut Line= 6
1664990.59114651349443.8709643331665063.00241901349512.693661332
1665132.06461684  349578.52095751665194.16685484349633.598603249
1665280.29430726349684.412806094  1665500.993669349814.627112582
#Sta/Elev= 30
       0 1105.37    18.4 1096.34    38.3 1084.42    63.8 1075.98    89.3 1065.33
   105.5 1056.71   173.3 1016.63   199.6  999.07   216.4  984.44   228.5  979.06
   236.4  973.48   240.5  972.19   259.1  971.88   280.6  964.44   296.5  964.08
   302.3  960.38     314  949.08     325944.4009   328.6   944.1   336.3  944.42
   345.6  947.37   442.5  948.01   475.6  946.76   509.7   948.8   524.3  957.68
   543.9  960.14   553.5   968.2     609 1002.99   624.3 1007.37   634.6  1014.8
#Mann= 5 ,-1,0
       0      .1       0     325    .045       0   336.3      .1       0
  448.32     .05       0  503.32      .1       0
Bank Sta=325,336.3
XS Rating Curve= 0 ,0
Exp/Cntr(USF)=0,0
Exp/Cntr=0.3,0.1

Type RM Length L Ch R = 1 ,24188   ,189.6,190.2,190.9
XS GIS Cut Line= 3
1664892.01537622349739.0345868421665209.81528751349953.108138197
1665267.19582705350095.456015129
#Sta/Elev= 30
       0  1041.7    14.6 1029.53    24.2  1022.6      30 1016.93    44.4 1010.96
    55.9 1001.84    77.3  987.53    87.6  979.28    96.6   973.2     102  970.73
     111  970.22   115.9  968.99   125.5  960.36   133.7  954.85   156.8  943.08
   159.3  942.07   164.5941.6384   173.7   941.6   174.2941.6042   202.7  944.75
   395.5     951     406  952.43   421.4  952.19   425.7  952.79     430  953.51
   433.7  955.08   442.9  960.91   455.9  966.28   490.4  977.95   536.7  995.37
#Mann= 4 ,-1,0
       0      .1       0   164.5    .045       0   174.2      .1       0
     360     .06       0
Bank Sta=164.5,174.2
XS Rating Curve= 0 ,0
Exp/Cntr(USF)=0,0
Exp/Cntr=0.3,0.1

Type RM Length L Ch R = 1 ,23997   ,509.5,508.6,507
XS GIS Cut Line= 6
1664823.02328378349806.4897944281664855.49266626349927.155490567
1664984.35100435350045.563718324 1665048.4069786350086.283125078
1665128.66436402350126.6806820681665216.28098667350166.858095159
#Sta/Elev= 30
       0  1034.4    35.3 1012.96    47.7 1009.26    72.5  995.19    80.8  989.38
    97.4  982.64     114  972.15   122.2  965.67     132   960.2   143.4  957.17
   163.2  958.93   168.4  957.69   180.1  951.53     191  941.56   197.1  939.35
   201.9  939.05   205.6  939.34   214.1  941.72   221.6  942.32     234  941.63
   279.2  942.99   380.3  942.79   442.7  943.85   451.7  946.67   466.7  956.84
   482.7  958.63   491.5  965.79   495.9  968.21   526.7  982.12   562.1 1000.08
#Mann= 5 ,-1,0
       0      .1       0   197.1    .045       0   205.6      .1       0
  425.86     .06       0  535.71      .1       0
Bank Sta=197.1,205.6
XS Rating Curve= 0 ,0
Exp/Cntr(USF)=0,0
Exp/Cntr=0.3,0.1

Type RM Length L Ch R = 1 ,23489   ,496.8,499.9,502.1
XS GIS Cut Line= 6
1664450.23100676350311.6149637551664535.50183359350350.691001087
1664615.01118901350387.3162559271664682.99792968350419.039289594
1664772.70444317350463.2308022531665002.12458801350577.381492585
#Sta/Elev= 30
       0 1111.49    15.3 1101.79    24.1 1097.69    50.4 1076.56    68.1  1075.1
    76.9 1072.58    86.6 1068.37   103.3 1058.78   125.3 1043.24   138.5 1036.61
   156.1 1031.97   182.6 1013.09   193.7 1008.49   235.5  975.49   266.5  958.85
   293.3  937.33   303.1  934.98   306.7  934.87   312.1  934.98   324.5  937.08
   476.3  936.57   482.2  938.88   494.1  950.12   507.6  959.67   512.1  960.94
     530  961.59   543.3  970.72   583.6  993.75   601.5 1005.65   612.6 1010.74
#Mann= 7 ,-1,0
       0      .1       0   303.1    .045       0   312.1      .1       0
  386.36     .06       0  451.36      .1       0  501.36     .06       0
  608.86      .1       0
Bank Sta=303.1,312.1
XS Rating Curve= 0 ,0
Exp/Cntr(USF)=0,0
Exp/Cntr=0.3,0.1

Type RM Length L Ch R = 1 ,22989   ,498.4,496.1,494.1
XS GIS Cut Line= 6
1664273.94198926350620.4398054181664341.38903284350691.530214429
1664400.97290318350760.5208900871664444.16966717350822.501409173
1664496.16464192350907.9211858361664628.91076751351127.107099175
#Sta/Elev= 30
       0 1098.26       9  1093.4      38 1070.98    61.3 1067.27    92.1 1043.28
   125.8 1026.87     146 1012.39   165.9 1001.43   198.9  979.06   211.5  965.45
   218.4  960.43   225.9  958.29   242.8  957.34   247.7  955.98     272  935.43
   276.5   933.3   309.2  929.56   313.9  929.31   318.6  929.54     328  932.36
   477.7   936.4   499.1  938.77   510.7   944.7   529.1  946.66   543.1  957.81
   560.3  962.05   574.8  968.29   585.2  970.01   603.9  981.41     621  988.72
#Mann= 5 ,-1,0
       0      .1       0   309.2    .045       0   318.6      .1       0
   469.7     .06       0   587.2      .1       0
Bank Sta=309.2,318.6
XS Rating Curve= 0 ,0
Exp/Cntr(USF)=0,0
Exp/Cntr=0.3,0.1

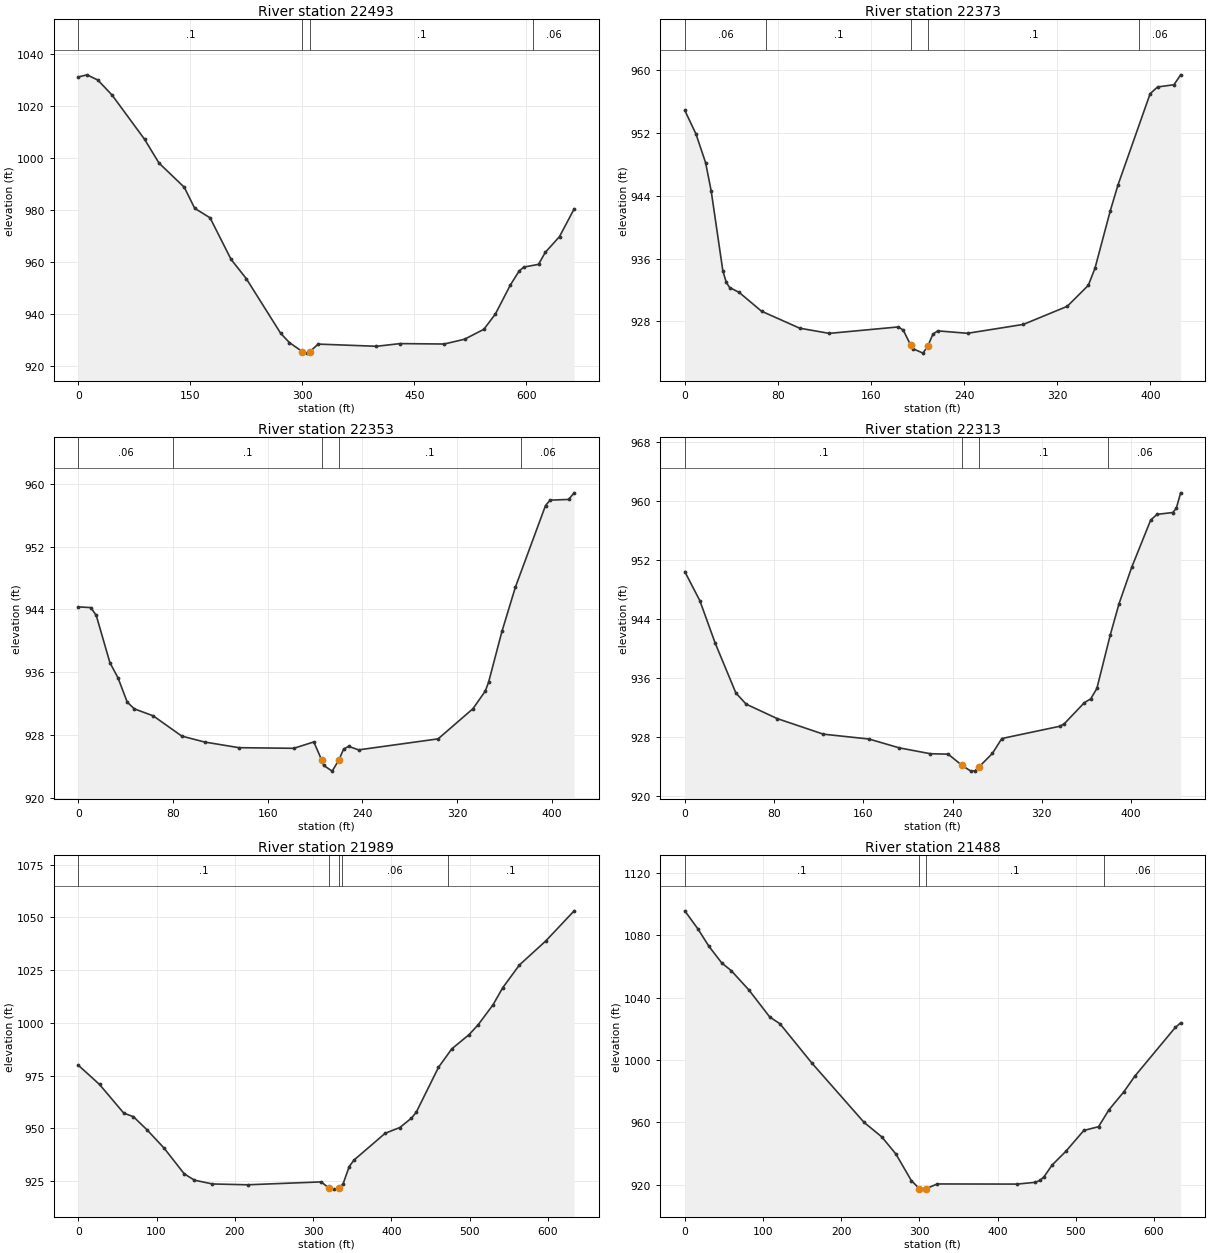
Type RM Length L Ch R = 1 ,22493   ,120.6,119.5,120.1
XS GIS Cut Line= 6
1663790.48363858350925.8414255831664002.40381843351070.130507082
1664087.72845092351123.5943109241664162.36412843351165.238256499
1664256.02929543351215.2309386731664352.57306559351278.089736834
#Sta/Elev= 30
       0 1031.07    11.6 1031.89    26.1 1029.89    45.3 1024.07    88.7 1007.11
     108  997.99   141.9  988.67   155.8   980.6   176.4  976.94   204.5  960.97
   224.9  953.56     271  932.53   282.6     929     300  925.51   305.6  924.94
   309.9925.5025   321.2  928.41   399.2  927.57   430.8   928.6   489.9  928.44
   517.2  930.29     543   934.1   558.4  939.96   578.6  951.18   590.2  956.49
   596.5  958.01   616.2  959.06   625.2  963.65   644.3  969.74   663.9  980.38
#Mann= 4 ,-1,0
       0      .1       0     300    .045       0   309.9      .1       0
  608.71     .06       0
Bank Sta=300,309.9
XS Rating Curve= 0 ,0
Exp/Cntr(USF)=0,0
Exp/Cntr=0.3,0.1

Type RM Length L Ch R = 1 ,22373   ,20.1,19.9,19.5
XS GIS Cut Line= 4
1663857.23904389351126.0824851731663934.29597448351177.277843165
1664168.10570221 351259.612645711664231.44016571351317.141450052
#Sta/Elev= 30
       0  954.83     9.6  951.83    17.9  948.17    22.7  944.57    32.7  934.43
    35.6  932.99    38.5  932.32    46.7   931.7    65.9  929.31    98.7  927.15
   124.1  926.49   183.5  927.31   187.7   926.9     194 925.014   196.2  924.53
   204.7  923.98   208.9  924.92   213.2   926.4   217.4  926.81   242.9   926.5
   290.9  927.63   328.6  929.93   346.7   932.6   352.4  934.76   365.6  942.09
   372.2  945.36   399.8  956.95   406.2  957.81   420.3  958.09     426  959.35
#Mann= 5 ,-1,0
       0     .06       0      70      .1       0     194    .045       0
   208.9      .1       0   390.4     .06       0
Bank Sta=194,208.9
XS Rating Curve= 0 ,0
Exp/Cntr(USF)=0,0
Exp/Cntr=0.3,0.1

Type RM Length L Ch R = 1 ,22353   ,41.6,40.7,38
XS GIS Cut Line= 5
 1663842.9887896351149.3051217881663927.43474093351197.333756606
1664087.35426126 351249.584688991664152.79987354351270.168389626
1664215.07876264351327.697193968
#Sta/Elev= 30
       0  944.33    10.5  944.24    15.1  943.26    26.7  937.23    33.5  935.32
    41.3  932.23    47.3  931.37    63.2  930.49    87.4  927.91   106.6  927.16
   135.7  926.44     182  926.36   198.9  927.17   205.7  924.82   207.3  924.18
   214.4  923.46   219.9  924.84   224.1  926.26   228.3  926.61   236.7  926.16
   303.9  927.56   333.3  931.39   343.7  933.62   346.5  934.75   357.8  941.21
   369.2  946.85   394.6   957.2   398.4  957.89   414.1  957.98   418.8  958.82
#Mann= 5 ,-1,0
       0     .06       0      80      .1       0   205.7    .045       0
   219.9      .1       0  373.99     .06       0
Bank Sta=205.7,219.9
XS Rating Curve= 0 ,0
Exp/Cntr(USF)=0,0
Exp/Cntr=0.3,0.1

Type RM Length L Ch R = 1 ,22313   ,314.1,323.7,326.7
XS GIS Cut Line= 4
1663808.43272993351192.8601685691663941.43510327 351269.33653324
1664137.61360395351275.0366349551664207.43984996351339.162779244
#Sta/Elev= 30
       0  950.39    13.5  946.45    27.3  940.68    45.8  933.94      55  932.43
    82.7  930.48   124.2  928.36   165.2   927.7   192.1  926.51   220.1  925.71
   236.1  925.65   248.6  924.12   256.4  923.35   260.1  923.38   264.1  923.97
   275.8  925.76   284.2  927.77   336.2  929.43   340.2  929.77   358.2  932.63
   363.9  933.15   369.4  934.55   381.5  941.85   389.3  946.05   400.6  950.96
   417.6  957.36   423.3  958.15   437.4   958.4   440.6  958.96   444.5  961.07
#Mann= 4 ,-1,0
       0      .1       0   248.6    .045       0   264.1      .1       0
  379.68     .06       0
Bank Sta=248.6,264.1
XS Rating Curve= 0 ,0
Exp/Cntr(USF)=0,0
Exp/Cntr=0.3,0.1

Type RM Length L Ch R = 1 ,21989   ,499.5,500.9,501.4
XS GIS Cut Line= 6
1663677.25387818351199.4947496651663719.83417359351301.433194086
1663754.40037742351386.7184565961663868.59175009351519.328099504
1663917.53062859351576.1609910881664035.80237368351713.504876509
#Sta/Elev= 30
       0  979.92    27.1   970.8      58  957.26    70.5   955.5    87.8  949.31
   109.5  940.69   135.4  928.44   148.4  925.46   171.4  923.66   216.3  923.27
   310.5  924.64   320.8921.5256     327  921.21   332.6  921.51   338.3  923.61
   346.1  931.82   352.2  934.94   392.2  947.69   410.8  950.38   425.8  954.86
   431.9  957.66   460.3  978.92   477.3  987.68   499.4  994.41   511.1  999.14
     530 1008.56   542.5  1016.7   563.8 1027.45   597.4  1038.8   633.7 1053.08
#Mann= 5 ,-1,0
       0      .1       0   320.8    .045       0   332.6      .1       0
   337.5     .06       0   472.5      .1       0
Bank Sta=320.8,332.6
XS Rating Curve= 0 ,0
Exp/Cntr(USF)=0,0
Exp/Cntr=0.3,0.1

Type RM Length L Ch R = 1 ,21488   ,497.7,499.1,505.7
XS GIS Cut Line= 6
1663216.93852584351399.8992045071663407.59824951351571.109492004
1663480.82316868351639.2363242511663527.89361259351699.203067839
 1663570.5309945351782.6645150931663627.88816325351874.131523758
#Sta/Elev= 30
       0 1095.63    16.9 1083.95    30.9 1072.85    47.3 1062.21    59.4 1057.28
      82 1044.89   108.7 1027.55   121.7 1023.24   162.6     998   229.3  960.02
     252   950.7   270.1  939.68   289.7  922.75   300.1  917.46   305.7  917.22
   308.6   917.5   322.9  920.54   425.1  920.45   448.5   921.6   454.5  922.86
   459.4  925.11   469.9  932.71   487.2  941.35   510.4  954.84   529.2  957.24
   542.6  968.11   561.5  979.56   575.6  989.63   627.4 1020.87   634.2 1023.77
#Mann= 4 ,-1,0
       0      .1       0   300.1    .045       0   308.6      .1       0
  536.22     .06       0
Bank Sta=300.1,308.6
XS Rating Curve= 0 ,0
Exp/Cntr(USF)=0,0
Exp/Cntr=0.3,0.1

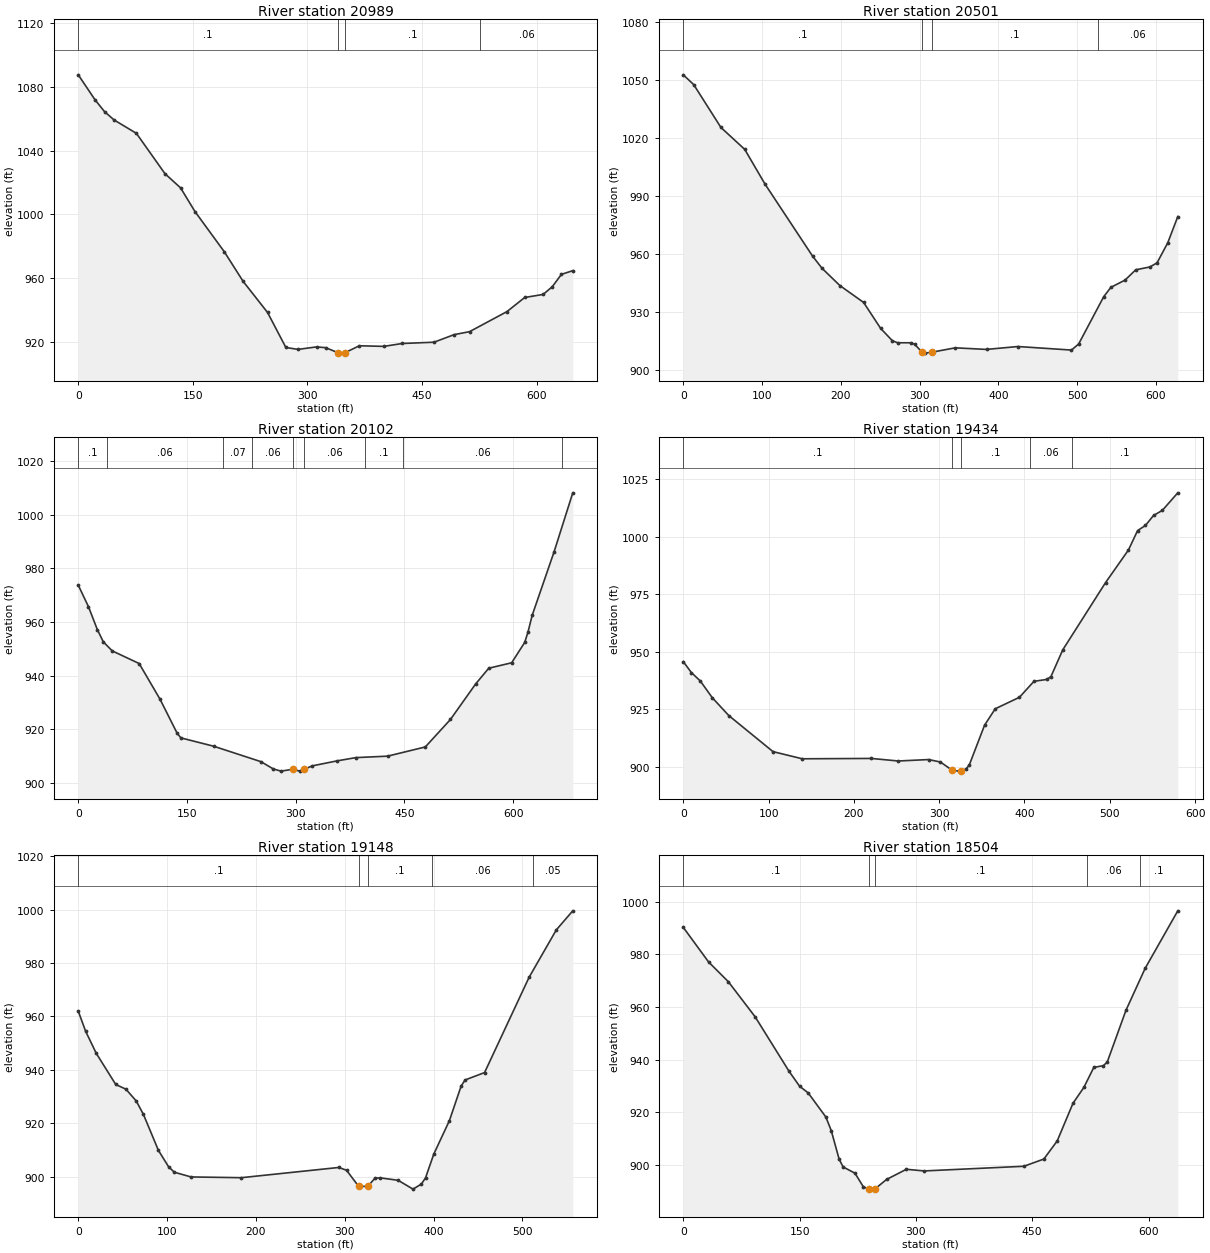
Type RM Length L Ch R = 1 ,20989   ,489.3,488,483.5
XS GIS Cut Line= 6
1663062.00018743351563.4736805111663092.92565051 351669.59256275
1663115.03781101351772.786254004  1663113.151988351847.825802088
1663095.79605159352109.751459345 1663089.5972451352203.296219751
#Sta/Elev= 30
       0 1087.57    21.9 1071.91    34.4 1064.44    46.9 1059.22    76.1 1050.82
   113.5 1025.48     134 1016.53   152.8 1001.68   191.3  976.36   215.8  957.86
   247.8   938.3   271.8  916.29   287.8  915.09   311.9  916.66   323.9  916.18
     340  913.03     344  912.75   349.2 913.024     368  917.37   400.1  916.99
   424.1   918.8   465.7   919.6     492  924.35   512.3  926.24   561.3  938.85
   584.5  947.71   608.6  949.61   620.6  954.49   632.6  962.24   647.4  964.55
#Mann= 4 ,-1,0
       0      .1       0     340    .045       0   349.2      .1       0
  526.13     .06       0
Bank Sta=340,349.2
XS Rating Curve= 0 ,0
Exp/Cntr(USF)=0,0
Exp/Cntr=0.3,0.1

Type RM Length L Ch R = 1 ,20501   ,399.3,399.5,390
XS GIS Cut Line= 6
 1662515.1574491351600.2304967491662550.21610601351687.178485587
1662648.38093592351930.6327230931662680.47339143351998.894069508
1662725.50512551352081.7456098351662772.50700001 352171.80284442
#Sta/Elev= 30
       0 1052.81    13.3 1047.72    47.8 1025.58      78 1014.25   103.8  996.25
   164.2  958.98   176.2   952.7   198.7  943.83   228.9  935.07   250.5  921.65
   265.3  915.31     272  914.22   289.3  914.21   293.6  913.44   303.1909.3486
   306.5  908.86   315.2  909.32   345.2   911.6   384.9  910.78   424.7  912.28
   492.7  910.44   501.8  913.59   533.6  938.04   542.7  942.89   560.7  946.64
   574.2  951.95   592.3  953.44   601.3  955.56   614.9  965.93   627.6  979.48
#Mann= 4 ,-1,0
       0      .1       0   303.1    .045       0   315.2      .1       0
  525.98     .06       0
Bank Sta=303.1,315.2
XS Rating Curve= 0 ,0
Exp/Cntr(USF)=0,0
Exp/Cntr=0.3,0.1

Type RM Length L Ch R = 1 ,20102   ,666.1,667.4,664.2
XS GIS Cut Line= 6
1662243.26995159351674.9300367831662207.99340801351820.739750249
 1662276.1947256351898.3481461261662330.28542576351945.383537566
1662433.76328692352011.2330855831662541.94468724352219.364692707
#Sta/Elev= 30
       0  973.71      14  965.74    26.3  957.16    34.6  952.55    46.9  949.21
      84   944.5   112.8  931.19   136.5  918.46   141.6  916.77   186.6  913.68
     252  907.91   269.1  905.19   279.7  904.38   295.6  905.06   305.4   904.4
   311.5  905.06   322.9  906.35   357.6  908.23     383  909.42   426.7  909.96
   478.8   913.4   513.5  923.66   548.3  936.92   566.3  942.75   597.9  944.78
   615.9  952.38   620.4  956.21   626.2  962.46   656.5  986.21   682.2 1008.15
#Mann= 9 ,-1,0
       0      .1       0      40     .06       0  200.02     .07       0
  240.02     .06       0   295.6    .045       0   311.5     .06       0
  395.01      .1       0  447.67     .06       0  667.67      .1       0
Bank Sta=295.6,311.5
XS Rating Curve= 0 ,0
Exp/Cntr(USF)=0,0
Exp/Cntr=0.3,0.1

Type RM Length L Ch R = 1 ,19434   ,285.1,286.3,288
XS GIS Cut Line= 4
1661698.06164233352206.3720010071661776.03950475352271.498183087
1661994.18069004352469.3023356961662135.41509183352586.649961999
#Sta/Elev= 30
       0  945.72     9.6  940.94      20  937.31    33.9   930.1    53.3  922.32
   105.2  906.63   139.5  903.52   220.5  903.67     252  902.56   287.7  903.19
   301.5  902.11   315.3898.5134   323.1  898.16     326898.2754   331.8  899.16
   335.4  900.94   353.2  918.11   365.7  925.24   394.1  930.24   411.1  937.17
   426.2     938     431  939.22   444.9  950.86     495  980.03   521.9  994.24
   532.6 1002.65   541.8 1004.88   551.3 1009.22   561.6 1011.42   579.7 1019.05
#Mann= 5 ,-1,0
       0      .1       0   315.3    .045       0     326      .1       0
  406.07     .06       0  456.07      .1       0
Bank Sta=315.3,326
XS Rating Curve= 0 ,0
Exp/Cntr(USF)=0,0
Exp/Cntr=0.3,0.1

Type RM Length L Ch R = 1 ,19148   ,640.7,643.9,641.6
XS GIS Cut Line= 6
1661534.93495506352345.980589385 1661588.1479385352401.448714019
1661603.95332151352416.4459440451661762.70255169  352671.1264993
1661801.54113791352756.3263902861661819.00134008352818.324314031
#Sta/Elev= 30
       0  961.97     8.3  954.45    20.2  946.22    42.2  934.53    53.7  932.76
    65.3  928.35    73.4   923.3    90.3  909.83   101.7  903.73   108.2  901.68
     127  899.92   183.6  899.64   293.4  903.47   302.1  902.41   315.6  896.44
   325.8  896.37     334  899.39   339.8  899.59   360.2  898.66   376.9  895.36
   386.3  897.25     391  899.57   400.3  908.47   417.9     921   431.1  933.93
   435.5  936.21   457.5  938.99   507.6  974.64   538.3  992.41   556.8  999.53
#Mann= 5 ,-1,0
       0      .1       0   315.6    .045       0   325.8      .1       0
  398.65     .06       0  512.39     .05       0
Bank Sta=315.6,325.8
XS Rating Curve= 0 ,0
Exp/Cntr(USF)=0,0
Exp/Cntr=0.3,0.1

Type RM Length L Ch R = 1 ,18504   ,242.1,242,241.5
XS GIS Cut Line= 6
1661151.46697636 352478.863579251661310.38759029352679.881549916
1661372.40551087352758.3275872541661418.91919736352817.162115253
1661454.67896837352908.0060936731661483.29472478353012.955030746
#Sta/Elev= 30
       0  990.22    32.7  977.05    58.2  969.55    92.8  956.19   136.5   935.5
     150  929.88   161.1  927.33   183.9  918.16   190.8  913.03     201  902.16
   206.1  899.21   221.4  896.84   232.3  891.62   239.7  890.82   243.7  890.78
     247890.8212   262.2  894.46   287.7  898.32   310.6  897.69   439.2  899.46
     465  902.21   482.2  909.08   502.6  923.41   516.6  929.42   529.4  937.01
   541.9   937.7   546.8  939.11   570.9  958.73   595.6  974.64   637.7   996.5
#Mann= 5 ,-1,0
       0      .1       0   239.7    .045       0     247      .1       0
  521.25     .06       0  588.88      .1       0
Bank Sta=239.7,247
XS Rating Curve= 0 ,0
Exp/Cntr(USF)=0,0
Exp/Cntr=0.3,0.1

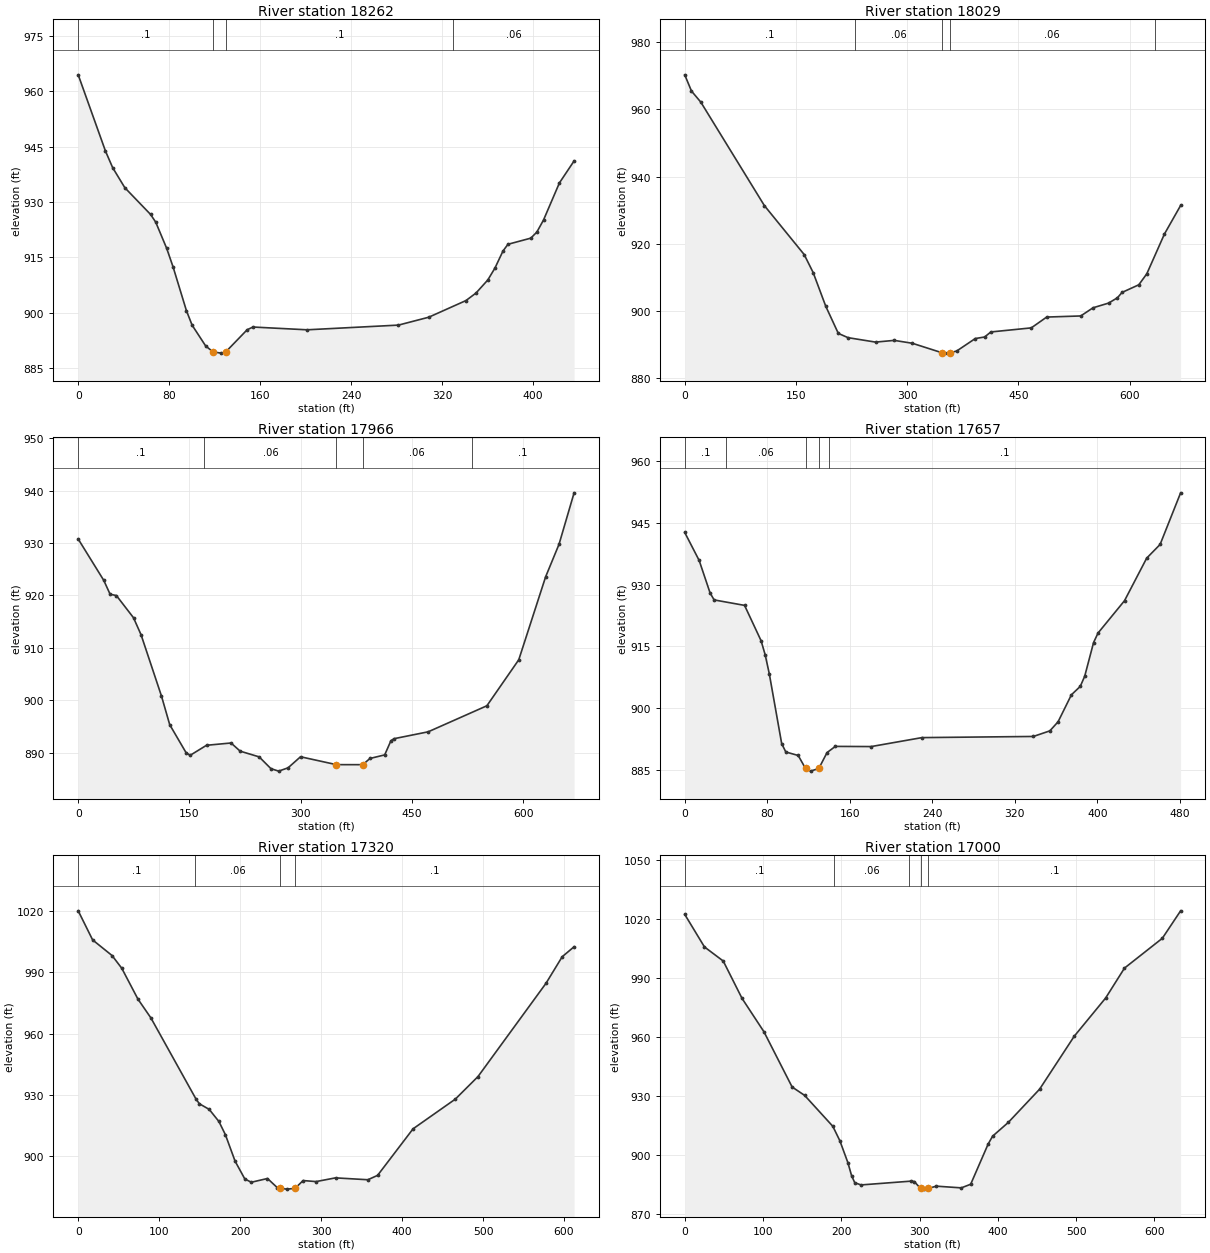
Type RM Length L Ch R = 1 ,18262   ,239.8,232.8,228.7
XS GIS Cut Line= 2
1661032.64252853352726.0928940711661326.21047237353048.695030151
#Sta/Elev= 30
       0  964.39      24  943.75    30.3  939.28      41  933.86    63.7  926.61
    68.2  924.53    77.8  917.47    83.5  912.38    95.2  900.59   100.2  896.67
   112.1  891.06   118.7  889.41   125.9  889.11   129.6  889.39   148.6  895.43
   153.7  896.17   201.3  895.42   281.7  896.69   308.3  898.82   341.1  903.33
   349.9  905.36   360.3   908.9   366.6  912.13   373.6   916.7     378  918.55
   398.1  920.21   403.4  921.84   409.3  925.11   423.3  935.16   436.2   941.1
#Mann= 4 ,-1,0
       0      .1       0   118.7    .045       0   129.6      .1       0
     330     .06       0
Bank Sta=118.7,129.6
XS Rating Curve= 0 ,0
Exp/Cntr(USF)=0,0
Exp/Cntr=0.3,0.1

Type RM Length L Ch R = 1 ,18029   ,76,63.2,55.8
XS GIS Cut Line= 5
1660705.20136041352890.6199834721660856.82436437353050.308040831
1661066.51575282352982.5615922551661203.62166066353022.886859265
1661239.10789563353100.311371924
#Sta/Elev= 30
       0  970.27     9.1  965.44    21.7  962.14   107.4  931.36   161.1  916.79
   173.2  911.43   190.2   901.4   207.1  893.34   220.2  892.07   257.3  890.75
   282.5  891.26   306.8  890.41   346.8  887.59     354  887.47   357.7  887.58
   366.6  888.08   391.8  891.81   404.4  892.27   412.8  893.77   467.3  894.98
   488.1   898.2     534  898.53   550.6  900.96   571.5  902.35   583.5  903.94
   589.7  905.53   612.3   907.8   623.1  911.07   646.9  922.92   668.7   931.4
#Mann= 5 ,-1,0
       0      .1       0   230.2     .06       0   346.8    .045       0
   357.7     .06       0  633.48      .1       0
Bank Sta=346.8,357.7
XS Rating Curve= 0 ,0
Exp/Cntr(USF)=0,0
Exp/Cntr=0.3,0.1

Type RM Length L Ch R = 1 ,17966   ,295.5,308.7,317.4
XS GIS Cut Line= 5
 1660652.7785133352947.0753572861660804.40151726353106.763414645
1661014.09290571353039.0169660691661151.19881354353079.342233079
1661186.68504851353156.766745738
#Sta/Elev= 30
       0  930.77    34.5  922.88      43  920.24    51.5  919.99    74.6  915.75
    84.8  912.49   112.3  900.81   123.4  895.35   145.4  890.02   150.9   889.5
     173  891.42   206.1  891.86   218.4   890.3     244  889.21   259.9  886.96
   270.3  886.49     283  887.12   299.8  889.23   348.1887.7273   383.8  887.72
   393.3   888.9   413.3  889.59   421.7  892.29   425.9  892.68   471.9  893.99
   551.1  898.96   594.1  907.74   630.3  923.56   648.4  929.78   668.7  939.59
#Mann= 5 ,-1,0
       0      .1       0     170     .06       0   348.1    .045       0
   383.8     .06       0  530.57      .1       0
Bank Sta=348.1,383.8
XS Rating Curve= 0 ,0
Exp/Cntr(USF)=0,0
Exp/Cntr=0.3,0.1

Type RM Length L Ch R = 1 ,17657   ,337.3,337.4,337.7
XS GIS Cut Line= 3
1660626.16383707353279.3555574481660987.47822948353276.129536087
1661098.77596643353319.680824458
#Sta/Elev= 30
       0  942.72      14   935.9    24.6  927.98    28.5   926.3      58  924.97
      74  916.38      78  912.94      82   908.3      94  891.31      98  889.28
     110  888.43   117.1885.2765     122  884.62     130  885.27     138  889.14
     146  890.64   180.8   890.6     230  892.78     338  893.06     354  894.42
     362  896.64   374.9   903.2   383.5  905.25   387.8  907.72   396.4  915.92
   400.7  918.23   426.4  926.11   447.9  936.47   460.9   939.8   480.8  952.37
#Mann= 5 ,-1,0
       0      .1       0      40     .06       0   117.1    .045       0
     130     .06       0     140      .1       0
Bank Sta=117.1,130
XS Rating Curve= 0 ,0
Exp/Cntr(USF)=0,0
Exp/Cntr=0.3,0.1

Type RM Length L Ch R = 1 ,17320   ,319.4,320,319.3
XS GIS Cut Line= 6
1660518.29730957353615.8153005291660699.54071348353614.280198609
1660874.53445799353612.7975900371660949.53168332353612.161764523
1661037.02855557353611.4206242761661130.77541533353610.626006445
#Sta/Elev= 30
       0 1020.16    17.8  1005.9    41.8  998.24    53.8     992    73.8  976.86
    89.8  967.64   145.8  927.66   149.8  925.53   161.8  922.81   173.8  916.87
   181.8  910.39   193.8   897.4   205.8  888.69   213.8  887.08   233.8  888.92
   245.8  884.47   249.8  884.08   257.8  883.71   267.8884.0699   277.8  887.91
   293.8  887.41   317.8  889.23   357.8  888.31   369.8  890.46   413.6  913.28
   465.8  927.84   493.8   938.9   577.8  984.63   597.8  997.65   612.5 1002.55
#Mann= 4 ,-1,0
       0      .1       0  143.75     .06       0   249.8    .045       0
   267.8      .1       0
Bank Sta=249.8,267.8
XS Rating Curve= 0 ,0
Exp/Cntr(USF)=0,0
Exp/Cntr=0.3,0.1

Type RM Length L Ch R = 1 ,17000   ,337.5,346,347.3
XS GIS Cut Line= 6
1660478.92398876353916.9492885021660735.13213776 353920.32198517
1660837.64964926353924.2376597521660920.24495651353920.203219011
1661013.77528125353912.5198354271661111.46603076353902.941770583
#Sta/Elev= 30
       0 1022.18    25.2 1005.65    49.2  998.49    73.2  979.53   101.2  962.57
   137.2  934.52   153.2  930.26   189.2  914.56   198.2  907.21   208.4  896.14
   213.2  889.45   217.2  885.94   225.2   884.8   289.2  886.73   293.2  886.53
   301.2  883.04   305.2  882.67   311.1     883   321.3  884.18   353.3  883.31
   365.3  885.15   387.6  905.55   393.3  909.56   413.4  916.56   453.4  933.45
   497.6  960.31   537.7  979.71   561.8  994.91   610.1 1010.03   633.5 1023.99
#Mann= 5 ,-1,0
       0      .1       0  191.24     .06       0  286.23      .1       0
   301.2    .045       0   311.1      .1       0
Bank Sta=301.2,311.1
XS Rating Curve= 0 ,0
Exp/Cntr(USF)=0,0
Exp/Cntr=0.3,0.1