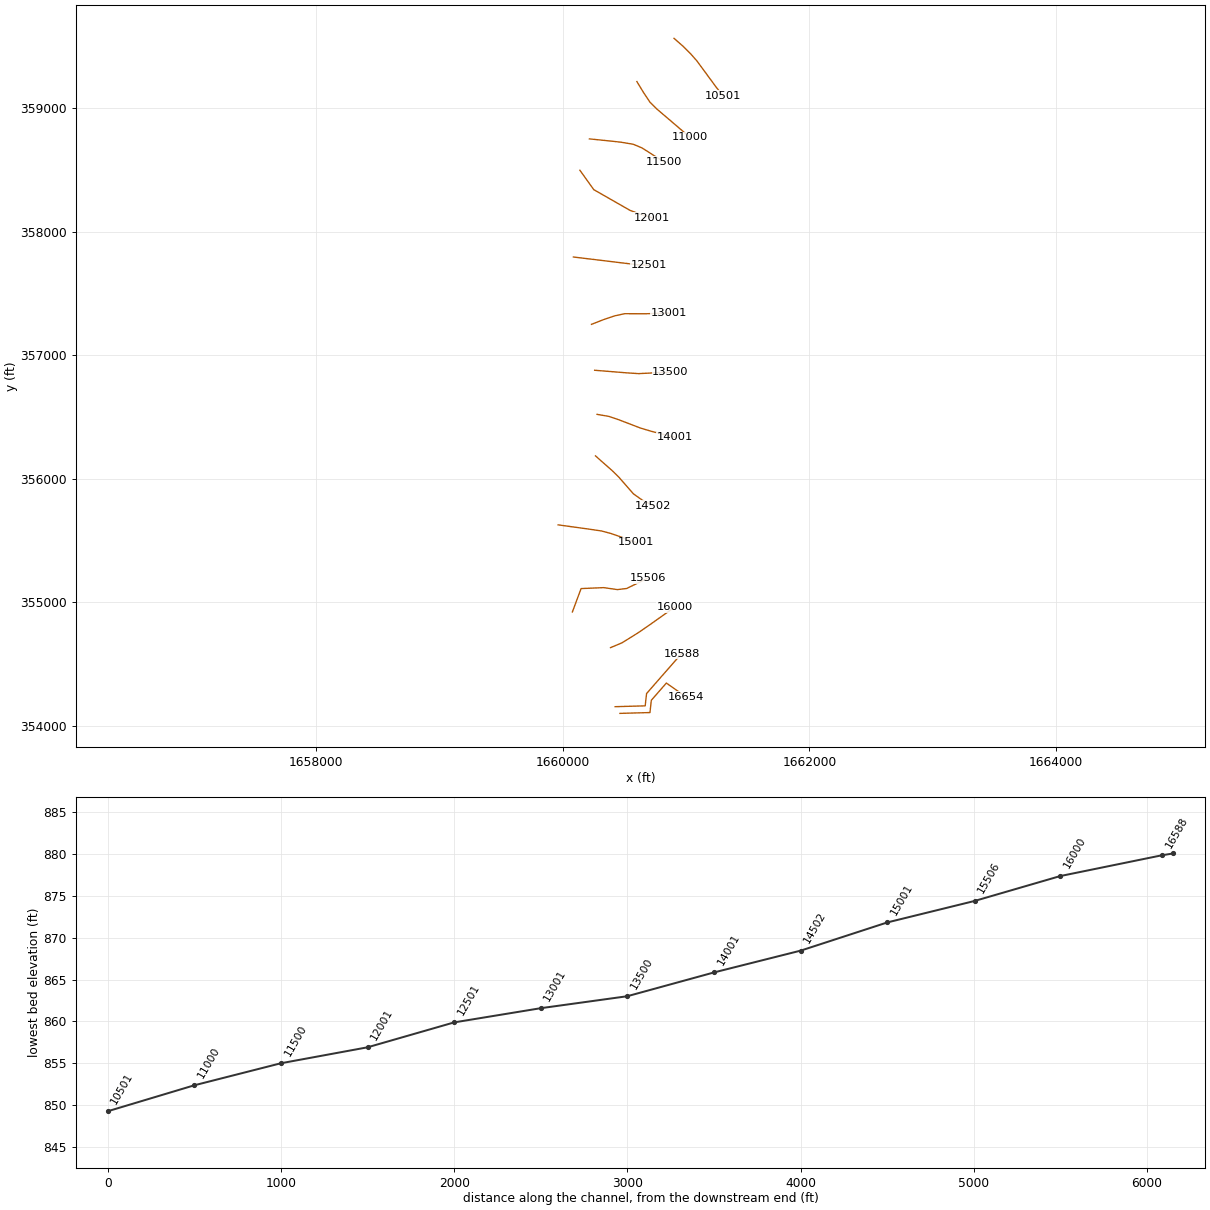
HEC-RAS study ARCHESFK.prj: ARCHESFK

--- ARCHESFK.g01 (geometry) --- (continued)

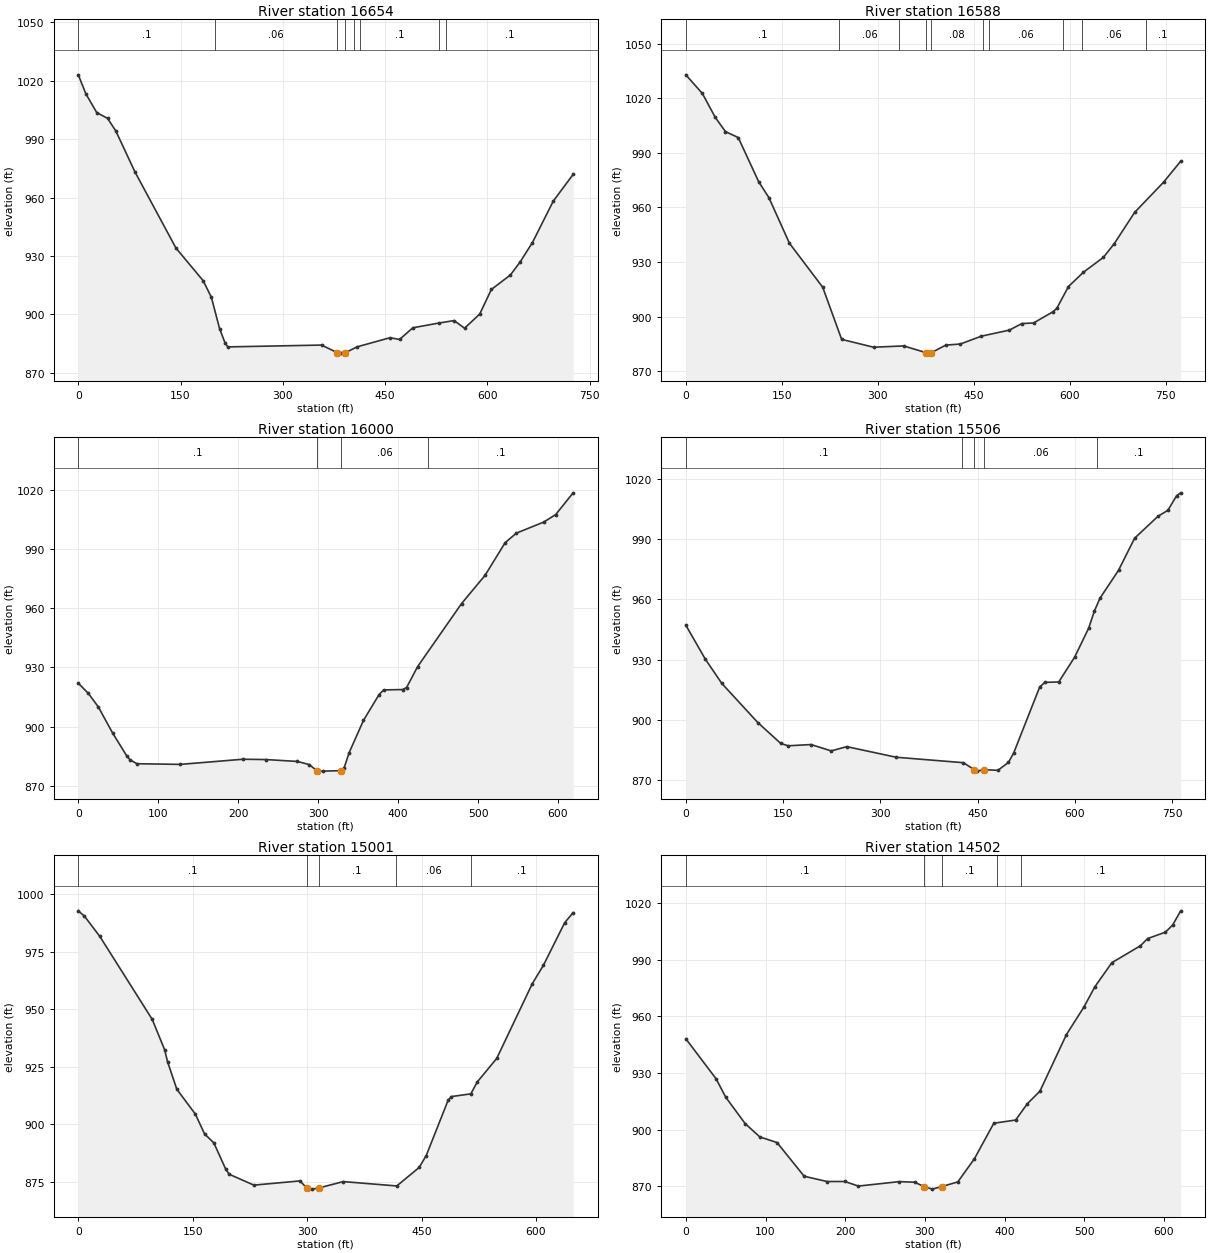
Type RM Length L Ch R = 1 ,16654   ,66.2,65.6,65.8
XS GIS Cut Line= 5
1660464.99552711354099.0946656581660708.38534172354105.732569693
1660719.44851511354205.3011302111660841.14342241354344.697114937
1661002.66575391 354231.85274635
#Sta/Elev= 30
       0  1023.1    11.1 1013.37    27.1 1003.68    42.9 1000.75    55.1  994.22
    83.1  973.22   143.2  934.11   183.2  917.29   195.2  908.76   207.2  892.72
   215.2  885.36   219.2   883.3   356.8  884.24   379.8  880.33   385.1   880.1
   391.8   880.3   408.8  883.33     457     888   471.2  887.13   490.6  893.12
   528.7  895.55   551.1  896.83   566.5   892.9   588.7  900.17   605.8  912.82
   633.7  920.25   647.7  926.79     666  936.91   696.6  958.22   725.7  971.93
#Mann= 8 ,-1,0
       0      .1       0     200     .06       0   379.8    .045       0
   391.8     .06       0  403.66     .08       0  413.66      .1       0
   528.7     .06       0   538.7      .1       0
Bank Sta=379.8,391.8
XS Rating Curve= 0 ,0
Exp/Cntr(USF)=0,0
Exp/Cntr=0.3,0.1

Type RM Length L Ch R = 1 ,16588   ,579.5,587.8,591.4
XS GIS Cut Line= 5
1660426.27442025354153.3042152741660669.66423485354159.942119309
1660680.72740824354259.5106798271660802.42231554354398.906664553
1660963.94464705354582.555342843
#Sta/Elev= 30
       0 1032.89    25.8 1022.67    45.9 1009.56    61.9 1001.67    81.9  998.41
   113.9  974.08   129.9  965.32   161.9   940.3   213.9  916.11   243.5  887.45
   293.3  883.14   340.4  883.83   375.1  880.18   380.8  879.88   383.8 880.163
   406.3  884.29     429  884.89   461.8   889.2   505.5  892.53   525.2  896.15
   543.4  896.46   573.7  902.61   579.7  904.48   597.9  916.47   621.4  924.38
   652.4  932.49   669.4     940   701.3  957.23   746.5  973.83   773.3  985.38
#Mann= 10 ,-1,0
       0      .1       0     240     .06       0  333.48     .08       0
   375.1    .045       0   383.8     .08       0  463.66      .1       0
  473.66     .06       0   588.7      .1       0   618.7     .06       0
   718.7      .1       0
Bank Sta=375.1,383.8
XS Rating Curve= 0 ,0
Exp/Cntr(USF)=0,0
Exp/Cntr=0.3,0.1

Type RM Length L Ch R = 1 ,16000   ,492.6,494.7,482.8
XS GIS Cut Line= 6
1660388.38512784354631.4819801751660480.50830318354669.946142092
1660555.11346893354716.0093701781660618.67174076354756.040130004
1660701.03574926354812.7686910931660910.00974075354961.072200254
#Sta/Elev= 30
       0  921.98    12.7  916.76    25.1  909.92    43.1  896.59    60.4  885.24
    64.7  883.15    73.4  881.14   127.6  880.81     206  883.42     235  883.25
   274.1   882.3   288.7  880.72   298.5   877.6   305.8  877.39     328877.6266
   332.4  878.93   338.8  886.79   356.7  903.12   376.2  916.21   381.9  918.56
   405.6  918.74   410.6  919.78   424.4  930.37   479.4  962.35   508.7  976.62
   533.9  993.22   547.9  998.03   582.2 1003.66   597.1 1007.45   618.9 1018.47
#Mann= 4 ,-1,0
       0      .1       0   298.5    .045       0     328     .06       0
  437.63      .1       0
Bank Sta=298.5,328
XS Rating Curve= 0 ,0
Exp/Cntr(USF)=0,0
Exp/Cntr=0.3,0.1

Type RM Length L Ch R = 1 ,15506   ,505.4,504.1,504.5
XS GIS Cut Line= 6
1660079.67670553354920.5036977421660150.40364842355110.151626512
1660333.90164101355117.9229364251660444.25935993355101.931170508
1660519.99083576 355111.022031591660689.70571943355193.983807921
#Sta/Elev= 30
       0  947.11    29.9  930.26    55.5  918.09     111  898.62   146.5  888.17
     158  887.03   193.2  887.65   224.2  884.48   248.2   886.6   324.4  881.33
   428.2  878.61   444.9875.1263     449  874.41   459.9  875.14   481.4  874.81
   497.7  878.77   505.6  883.35   545.9  916.35   553.9  918.63   575.2  918.81
   599.8   931.2   621.4  945.62   630.1  954.04   638.7  960.46   667.4  974.41
   692.2  990.38   728.4 1001.37   743.5 1004.28   756.9  1011.5   763.3 1013.01
#Mann= 5 ,-1,0
       0      .1       0  426.16     .06       0   444.9    .045       0
   459.9     .06       0  633.95      .1       0
Bank Sta=444.9,459.9
XS Rating Curve= 0 ,0
Exp/Cntr(USF)=0,0
Exp/Cntr=0.3,0.1

Type RM Length L Ch R = 1 ,15001   ,503.6,499.6,490.2
XS GIS Cut Line= 6
   1659964.08742355626.5111580941660217.91532442355591.363590583
1660316.83802684355576.6910477581660392.77750751355556.409592256
1660491.60670617355521.8184540871660594.46017501355484.912688002
#Sta/Elev= 30
       0  992.77     8.1  990.45    28.3  981.62    96.9  945.62   113.1   932.5
   117.1  927.15   129.2  915.23   153.5  904.44   165.6  895.81   177.7  891.96
   193.3  880.53   197.9   878.3   230.2  873.58   290.8  875.41   299.4  872.32
     307  871.84   315.1  872.32   347.4  875.11   417.6  873.22   446.9  881.24
   456.2  886.43     485  910.53   489.2  912.06   514.7  913.24   523.1  918.41
   548.6  928.62   595.3  961.14   609.8  969.08   637.8  987.65   648.8  991.99
#Mann= 5 ,-1,0
       0      .1       0   299.4    .045       0   315.1      .1       0
  416.25     .06       0  514.86      .1       0
Bank Sta=299.4,315.1
XS Rating Curve= 0 ,0
Exp/Cntr(USF)=0,0
Exp/Cntr=0.3,0.1

Type RM Length L Ch R = 1 ,14502   ,495,500.4,505.2
XS GIS Cut Line= 6
1660267.14718135356185.1301195921660404.66691943356063.669732586
1660458.81641743356010.0651810021660574.27911301 355877.81347701
1660646.77634335355826.3175170121660733.12623626355782.531843424
#Sta/Elev= 30
       0  948.17      38  926.94      50  917.25    74.5  903.18    92.9  896.13
   114.5  893.16   148.5  875.29   177.3   872.5   199.5  872.52   216.5  870.09
   267.8  872.44   287.2  872.14   298.7  869.84   309.3  868.47   321.3  869.83
   341.3   872.3   362.1  884.53   386.5  903.39   413.9   905.1   428.6  913.74
   444.4  920.41   477.6  950.36   499.6  965.01   513.4  975.78   534.7  988.51
   570.5  997.47   579.5 1001.27   601.9 1004.67   610.9 1008.43     621 1015.98
#Mann= 5 ,-1,0
       0      .1       0   298.7    .045       0   321.3      .1       0
  390.22     .06       0  420.22      .1       0
Bank Sta=298.7,321.3
XS Rating Curve= 0 ,0
Exp/Cntr(USF)=0,0
Exp/Cntr=0.3,0.1

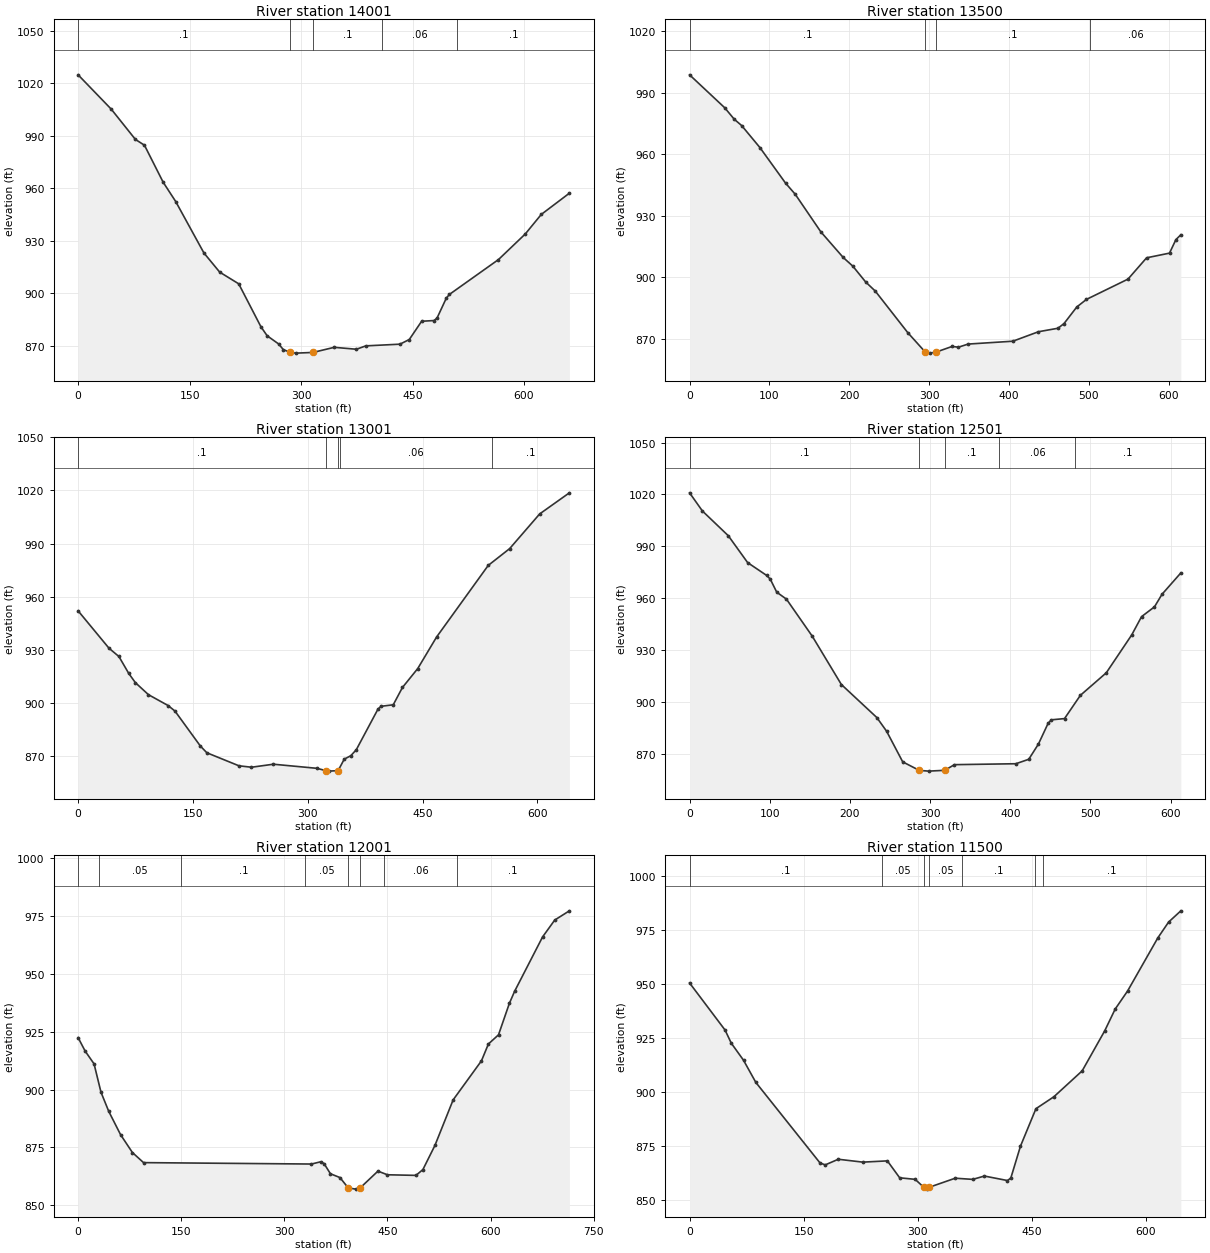
Type RM Length L Ch R = 1 ,14001   ,487.9,501.3,504.1
XS GIS Cut Line= 6
1660280.06677492356521.5635018351660373.46324167356505.667208165
 1660456.4191125356477.7729070041660631.32394642356410.840954259
1660718.25946809356384.6726995111660912.79221551356335.610133588
#Sta/Elev= 30
       0 1024.74    44.7 1005.09    77.1  987.86    89.3  984.54   114.4  963.46
   131.3  952.42   169.3  923.03   190.5  912.11   216.1  905.43     246   880.9
   254.4  875.75   269.9  871.07     276  867.92   285.3  866.27   293.2  865.86
     316866.2494   344.6  869.17   374.5  868.08   387.1     870     433  870.97
   445.6  873.63   462.2  884.05   478.8  884.46   482.9  885.83   495.3  897.16
   499.5  899.35   565.6  919.27   601.6  933.86   623.2  945.04     661  957.16
#Mann= 5 ,-1,0
       0      .1       0   285.3    .045       0     316      .1       0
  409.54     .06       0  510.32      .1       0
Bank Sta=285.3,316
XS Rating Curve= 0 ,0
Exp/Cntr(USF)=0,0
Exp/Cntr=0.3,0.1

Type RM Length L Ch R = 1 ,13500   ,497,499.3,498.9
XS GIS Cut Line= 6
  1660260.299426356878.989624262 1660515.7047551356858.202264249
1660615.50639276356851.701621085 1660691.0446275356855.264606088
1660779.34858476356860.2199767531660874.30344734356862.060852334
#Sta/Elev= 30
       0  998.74      44  982.68      56  977.06    65.2  974.01    88.1  963.26
   120.2  945.93   132.3  940.51   164.4  922.16   192.4  909.67   204.5  905.41
   220.5  897.73   232.6  893.26   273.3  872.99   295.2 863.525   300.8  863.01
   308.8  863.52   328.8  866.27   336.8  865.91   348.9  867.43   404.9  868.82
     437  873.45   461.4  875.14     469  877.44     485  885.53   497.1  889.22
   549.1  899.11   572.4   909.5   601.1  911.78   609.1  918.37   615.3  920.74
#Mann= 4 ,-1,0
       0      .1       0   295.2    .045       0   308.8      .1       0
  501.89     .06       0
Bank Sta=295.2,308.8
XS Rating Curve= 0 ,0
Exp/Cntr(USF)=0,0
Exp/Cntr=0.3,0.1

Type RM Length L Ch R = 1 ,13001   ,503.3,499.9,493.5
XS GIS Cut Line= 6
1660234.48779784357250.9035785941660330.24974543357288.369054839
1660421.50087526357319.4772603361660502.93772025357337.159639671
1660680.92719367357336.8712544291660862.06397051357342.526098758
#Sta/Elev= 30
       0  952.07    40.4  930.94    53.3  926.29    66.2   916.7    74.8  911.54
    91.9  904.74   117.5  898.62   126.5  895.51   159.7  875.76   168.2  871.94
   210.1  864.59   226.5  863.78   255.1  865.48   311.7  863.18   323.7  861.86
   327.7  861.58   339.7  861.87   347.7  868.35   356.2  870.27   363.4  873.64
   391.7  896.54   395.7  898.17   411.7  899.03   423.7  908.79   443.7  919.48
   468.3  937.27   535.8  977.71   563.8  987.19     603 1006.77   641.8 1018.68
#Mann= 5 ,-1,0
       0      .1       0   323.7    .045       0   339.7      .1       0
  342.57     .06       0  540.56      .1       0
Bank Sta=323.7,339.7
XS Rating Curve= 0 ,0
Exp/Cntr(USF)=0,0
Exp/Cntr=0.3,0.1

Type RM Length L Ch R = 1 ,12501   ,499.1,500,496.6
XS GIS Cut Line= 6
1660088.21479642 357796.537986011660181.28350793357785.255856335
  1660342.602411 357765.701433511660441.87583451357753.667336836
1660603.19506568 357734.113242091660696.96292275357728.598817423
#Sta/Elev= 30
       0 1020.94      16 1010.43    48.3  996.11    72.4  980.56    96.2  973.11
   100.6  971.02   108.7  963.44   120.8  959.42     153  937.97   189.3  910.01
   233.5  890.91   245.7  882.99   265.8  865.25   286.4860.3228   298.1  859.88
   318.2  860.35   330.3  863.62   406.9  864.16     423  866.73   435.1  875.57
   447.1   887.5   451.2  889.57   467.6  890.28   487.4  903.75   519.7  916.78
   551.4  938.69   563.7  949.29   579.8  954.95   589.2  962.22   612.7   974.6
#Mann= 5 ,-1,0
       0      .1       0   286.4    .045       0   318.2      .1       0
  386.25     .06       0  481.25      .1       0
Bank Sta=286.4,318.2
XS Rating Curve= 0 ,0
Exp/Cntr(USF)=0,0
Exp/Cntr=0.3,0.1

Type RM Length L Ch R = 1 ,12001   ,495.4,500.5,501.9
XS GIS Cut Line= 6
1660140.74168092358499.4437978271660253.11604142358342.298705503
1660481.03061184358212.0634016691660546.14826375358174.852518082
1660628.81968634 358143.669509591660720.51176018358116.312937006
#Sta/Elev= 30
       0  922.47    10.2  916.66    23.2  911.11    33.3  898.83    44.6  890.54
    61.8  880.46      79  872.74    95.2  868.37   339.5  867.76   353.3  868.76
   357.9  867.91   367.1  863.55   380.9  861.91   393.1  857.39     404   856.9
   410.2857.3914   436.2  864.69     450  863.11   491.5  862.85   501.6  865.36
   519.1  875.81   545.6  895.53   586.8  912.43   596.9  919.71   611.6  923.68
   627.4  937.29     635   942.5   675.7  966.04   693.4  973.35   714.7  977.34
#Mann= 8 ,-1,0
       0      .1       0      30     .05       0     150      .1       0
  330.69     .05       0   393.1    .045       0   410.2     .05       0
  445.69     .06       0  550.69      .1       0
Bank Sta=393.1,410.2
XS Rating Curve= 0 ,0
Exp/Cntr(USF)=0,0
Exp/Cntr=0.3,0.1

Type RM Length L Ch R = 1 ,11500   ,499.2,500.4,496.9
XS GIS Cut Line= 6
1660217.60134867358753.4501141761660399.15446326358734.937355921
1660473.97255509 358726.53120476 1660572.6117935358710.090292752
1660643.15561567358680.6644985821660821.74252884358567.251011506
#Sta/Elev= 30
       0  950.37    46.7  928.55    54.8  922.52    70.9  914.62    87.1  904.36
   171.4  867.13   178.3   866.2   195.5  868.81   227.7  867.48     260  868.06
   276.2  860.23   296.5  859.52   307.9 855.849   312.7  854.99   315.3855.8844
   349.2  860.04   372.2   859.5   387.6  861.04   417.9  858.96   422.3  860.13
     435  874.89   455.3   892.2   478.9  897.72   516.1  909.71   545.7  928.21
   559.5  938.31   575.8  946.66   615.5   971.2   629.7  978.54   645.8  983.74
#Mann= 7 ,-1,0
       0      .1       0  252.49     .05       0   307.9    .045       0
   315.3     .05       0  357.78      .1       0  454.22     .06       0
  464.22      .1       0
Bank Sta=307.9,315.3
XS Rating Curve= 0 ,0
Exp/Cntr(USF)=0,0
Exp/Cntr=0.3,0.1

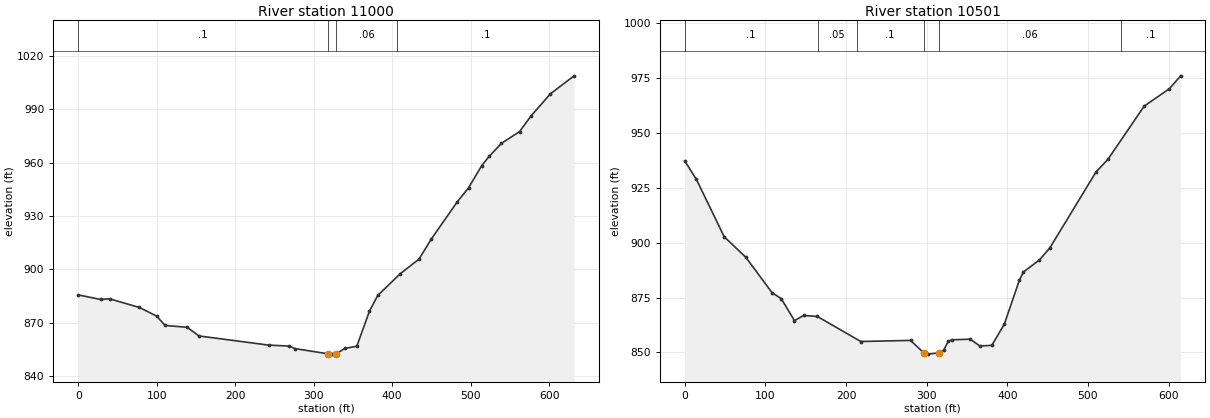
Type RM Length L Ch R = 1 ,11000   ,501.7,499,497.4
XS GIS Cut Line= 6
1660602.23870276359217.8035161791660656.49745251359128.812880501
1660709.88218826359048.9774102571660763.46278976358996.045757592
1660896.60884893358882.4803679291661034.50981984358764.858555928
#Sta/Elev= 30
       0  885.68    28.5  883.09    40.1  883.45      78  878.59    99.9  873.75
   110.7  868.48   138.8  867.45   153.9  862.57   242.8  857.41   269.2  856.88
   275.7  855.48   318.5  852.53   323.8  852.35     329  852.51   339.5  855.55
     355  856.81   371.1  876.56   381.6  885.35   410.4  897.62   434.2  905.79
   449.9   917.1   482.8  937.93   497.3  945.88     514  958.29   523.5  963.57
   539.3  970.92   562.3  977.49   576.9   986.3   601.5  998.72   631.8 1008.89
#Mann= 4 ,-1,0
       0      .1       0   318.5    .045       0     329     .06       0
  405.58      .1       0
Bank Sta=318.5,329
XS Rating Curve= 0 ,0
Exp/Cntr(USF)=0,0
Exp/Cntr=0.3,0.1

Type RM Length L Ch R = 1 ,10501   ,478.1,465.5,457.7
XS GIS Cut Line= 6
1660903.27353376 359568.09677884 1660974.4968165   359505.526694
1661037.30968301359443.5353481771661087.25446501359387.047928333
1661242.69837984359175.4804380831661301.02142592359101.935965762
#Sta/Elev= 30
       0  937.26    14.5  928.82      49  902.69    75.7   893.4   108.3  877.23
   119.6  874.56   136.1  864.52   147.5  866.87   164.5   866.4   218.3     855
     280   855.5   296.4  849.83   301.4  849.25     315849.8112   320.9  850.91
   326.6  855.01   331.3  855.76   353.9  856.07   366.1  852.94   380.8  853.26
   396.3  862.91   415.1   883.1     420  886.67   439.8  892.15   452.7  897.61
   509.8  932.12   524.8  938.02   569.7  962.21     601  970.17   614.9  976.03
#Mann= 6 ,-1,0
       0      .1       0   164.8     .05       0  213.06      .1       0
   296.4    .045       0     315     .06       0     541      .1       0
Bank Sta=296.4,315
XS Rating Curve= 0 ,0
Exp/Cntr(USF)=0,0
Exp/Cntr=0.3,0.1