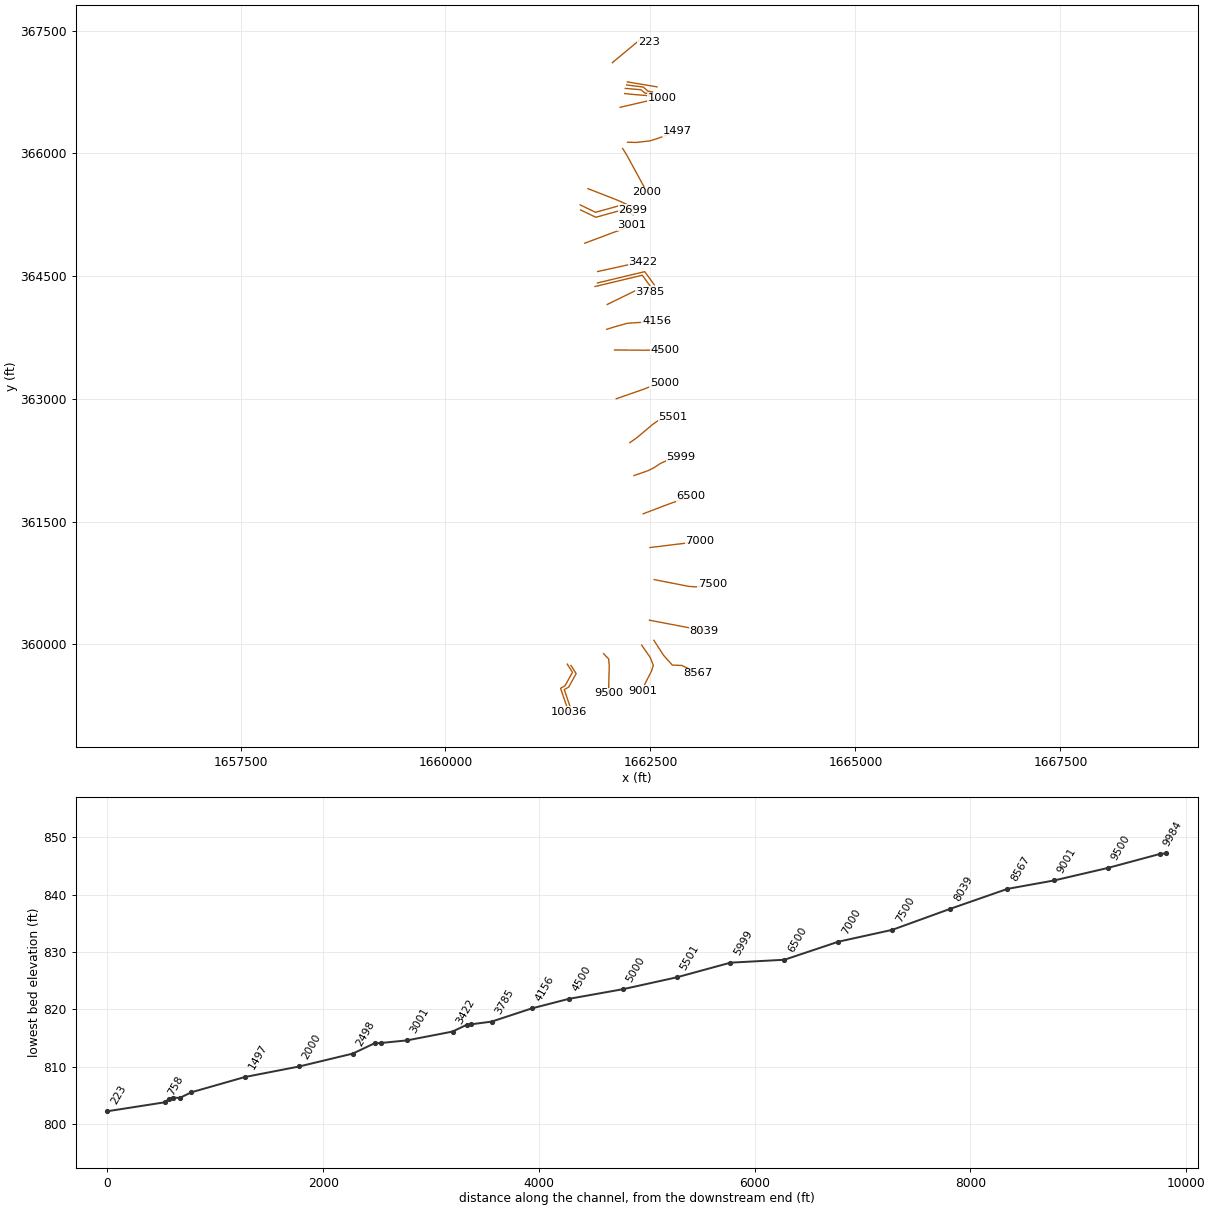
HEC-RAS study ARCHESFK.prj: ARCHESFK

--- ARCHESFK.g01 (geometry) --- (continued)

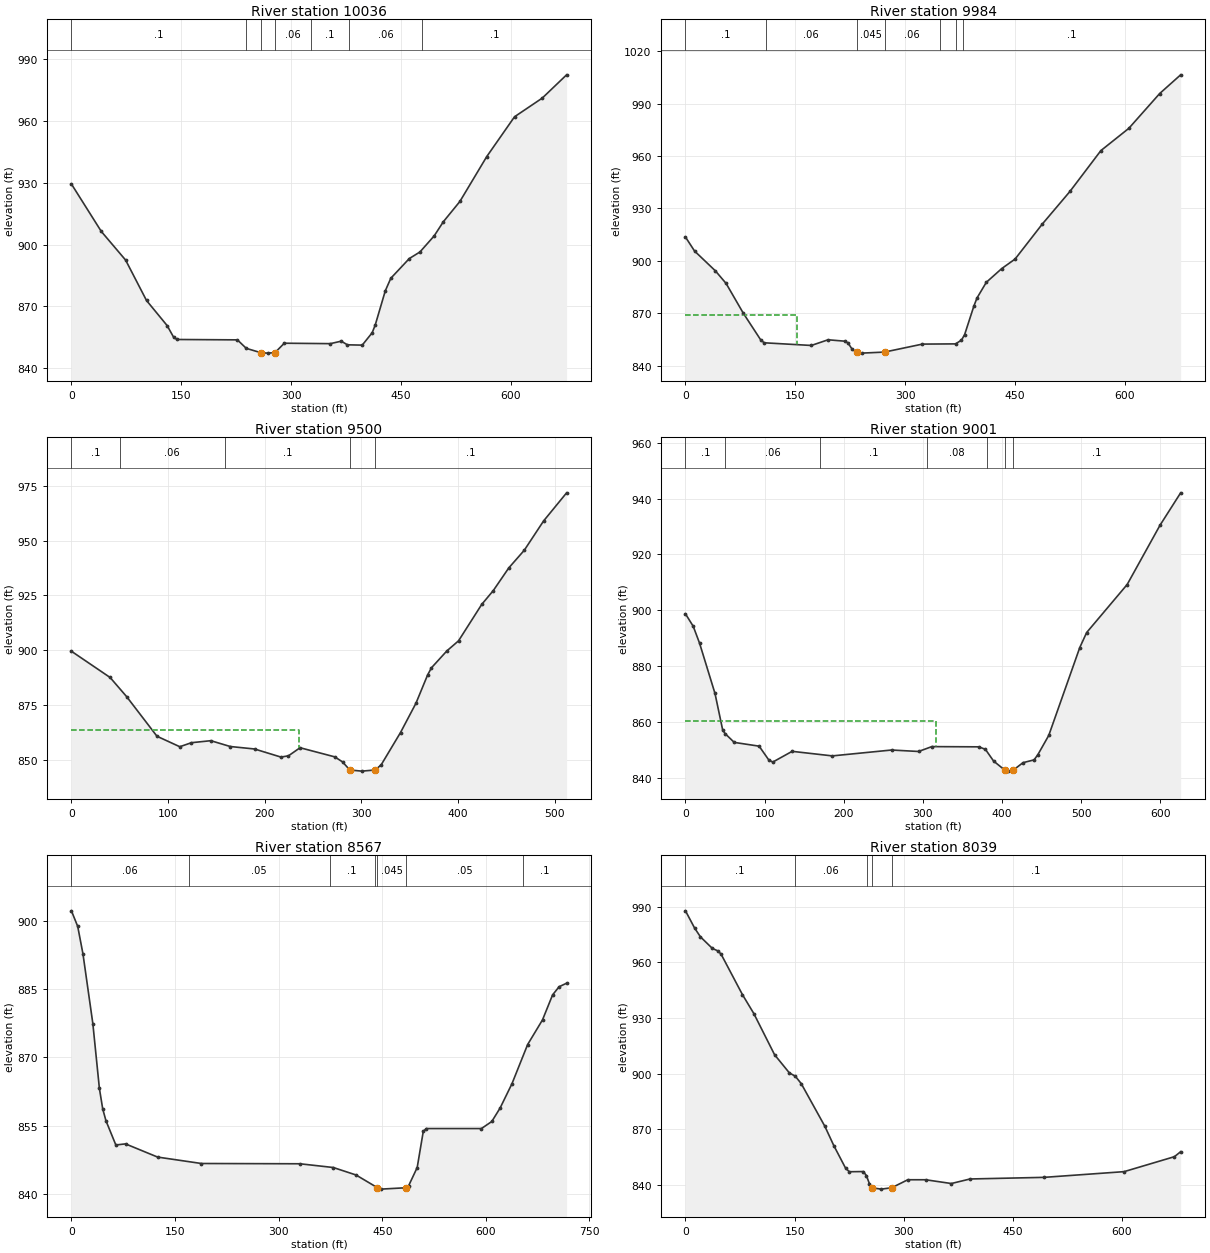
Type RM Length L Ch R = 1 ,10036   ,57.3,51.7,49
XS GIS Cut Line= 5
1661485.41073939 359758.899443261661549.13461812359659.330882742
1661457.53154244359494.0470722811661403.76451976359464.176504125
1661503.33308028359173.436307411
#Sta/Elev= 30
       0  929.44    40.8  906.38      74  892.45   102.5  872.82   130.6  860.64
   139.7  854.85   144.3  853.85   226.6  853.67   238.7  849.54   258.6  847.43
   267.8  847.22   277.9847.4714   290.6  852.04   353.5  851.83   368.3  853.03
   376.8  851.26     397  851.11   410.6  857.14   414.8  860.96   428.5  877.53
     436  883.62   461.3  893.22   475.8  896.41   495.2  904.22   507.8  911.14
   530.3  920.96     567   942.8   604.9  962.14   642.7  971.21     676  982.54
#Mann= 7 ,-1,0
       0      .1       0  238.21     .06       0   258.6    .045       0
   277.9     .06       0  327.18      .1       0  378.69     .06       0
  478.69      .1       0
Bank Sta=258.6,277.9
XS Rating Curve= 0 ,0
Exp/Cntr(USF)=0,0
Exp/Cntr=0.3,0.1

Type RM Length L Ch R = 1 ,9984    ,469.7,483.8,489.6
XS GIS Cut Line= 5
1661530.21659162359742.9684735771661593.94047035359643.399913059
1661502.33739468359478.116102598  1661448.570372359448.245534442
1661548.13893251359157.505337728
#Sta/Elev= 30
       0   913.6    12.4  905.58    40.9  894.21    55.5  887.01    78.9  870.02
   102.6  854.79   107.4  853.06   171.8  851.53   194.7  854.78   217.5  853.98
   221.7  853.05   227.6  849.34   233.5  847.73   240.4  847.14   271.7  847.74
   323.5  852.31   368.7  852.43   376.8  854.59   381.1  857.76   393.8  874.18
     398  878.72   410.7  887.68   431.8  895.56     450  901.01   486.8  920.86
   524.8  939.67   567.1  963.08   605.2   975.8   647.4  995.75     676 1006.45
#Mann= 7 ,-1,0
       0      .1       0     110     .06       0   233.5    .045       0
   271.7     .06       0  347.18      .1       0  368.69     .06       0
  378.69      .1       0
#XS Ineff= 2 , 0
          151.87  869.12
Permanent Ineff=
       F       F
Bank Sta=233.5,271.7
XS Rating Curve= 0 ,0
Exp/Cntr(USF)=0,0
Exp/Cntr=0.3,0.1

Type RM Length L Ch R = 1 ,9500    ,502.8,499.4,499.3
XS GIS Cut Line= 6
 1661928.0639862359887.1048915591661990.15101935359824.033777991
1661997.55612209359738.1761630921661993.01183984359563.235240012
1661991.06400909359488.260652423  1661988.792032359400.790026844
#Sta/Elev= 30
       0  899.48      40  887.49    57.1  878.74    88.5  860.63   112.1  855.84
   124.1  857.68   144.2   858.6   164.3  855.94   189.4  854.81   216.7  851.11
   224.5  851.69   236.5  855.38   272.4  851.21   280.4  848.91     288 845.199
   300.4  844.69   314.2  845.21   320.4  847.57   340.4  862.33   356.4  875.74
   368.4  888.62   372.4  891.91   388.4  899.66   400.4  904.23   424.4  920.88
   436.4  927.23   452.4  937.57   468.4  945.63   488.4  959.03   512.2  971.88
#Mann= 5 ,-1,0
       0      .1       0      50     .06       0   158.5      .1       0
     288    .045       0   314.2      .1       0
#XS Ineff= 2 , 0
           235.9  863.68
Permanent Ineff=
       F       F
Bank Sta=288,314.2
XS Rating Curve= 0 ,0
Exp/Cntr(USF)=0,0
Exp/Cntr=0.3,0.1

Type RM Length L Ch R = 1 ,9001    ,404.2,433.3,460.1
XS GIS Cut Line= 6
1662393.07698597359991.1010484591662494.08203192359846.195304006
 1662534.6944835359745.3680778441662512.23816359359672.643813834
1662432.01752351359516.8718156671662407.45228392359431.609847084
#Sta/Elev= 30
       0  898.76     9.8  894.31    17.8  888.27    37.3  870.29      47  857.25
      50  855.95    61.6  852.78    93.1  851.43   105.5  846.41   110.4  845.75
   134.8  849.58   185.6  847.95   260.4  850.05   294.6  849.53   311.3  851.27
   370.9  851.19   379.1  850.28   389.4   846.1   403.4   842.9     408   842.5
   414.2  842.86   426.6  845.53   440.5  846.52   445.2  848.32   459.1  855.27
   498.3   886.7     507  892.08   558.2  909.26   599.8  930.51   625.8  942.06
#Mann= 7 ,-1,0
       0      .1       0      50     .06       0     170      .1       0
  305.33     .08       0  381.45      .1       0   403.4    .045       0
   414.2      .1       0
#XS Ineff= 2 , 0
          316.08  860.29
Permanent Ineff=
       F       F
Bank Sta=403.4,414.2
XS Rating Curve= 0 ,0
Exp/Cntr(USF)=0,0
Exp/Cntr=0.3,0.1

Type RM Length L Ch R = 1 ,8567    ,526.5,528.4,526.9
XS GIS Cut Line= 5
1662541.59961061360050.5492786751662663.29451791359862.475331029
1662767.28834778359747.4183277631662882.34535105359742.993058407
1663083.69510676359647.849767245
#Sta/Elev= 30
       0  902.17     9.1  898.75    16.7  892.71      31  877.41    40.5  863.14
    45.3  858.66      50  856.05    64.3  850.73    78.3  850.97   124.8  848.07
   188.2  846.66   330.8   846.6   379.1  845.78     412  844.14   442.9841.3557
     448  841.03     484  841.33     488  841.71   500.6  845.78   509.4  853.72
   513.9  854.34   593.6  854.34   608.6  855.89   620.6  858.84   637.8  864.19
   660.5   872.8     682  878.21   696.6   883.7     706  885.49   716.9  886.27
#Mann= 7 ,-1,0
       0     .06       0     170     .05       0  374.01      .1       0
   439.1     .05       0   442.9    .045       0     484     .05       0
  654.24      .1       0
Bank Sta=442.9,484
XS Rating Curve= 0 ,0
Exp/Cntr(USF)=0,0
Exp/Cntr=0.3,0.1

Type RM Length L Ch R = 1 ,8039    ,537.1,538.9,536.6
XS GIS Cut Line= 2
1662487.83456217 360295.906120691663156.54193158 360168.06500595
#Sta/Elev= 30
       0   987.9    12.5  978.63    20.6  973.83    36.9  967.62    45.1  966.15
    49.2  964.31    78.3  942.65      94  932.39   122.5  910.17   142.8  900.36
     151  898.55   159.1  894.59   191.7  871.45   203.9   861.1   220.2  848.83
   225.3  846.96   244.6  847.05   248.7  844.88   252.8   840.6   256.8  838.25
   269.1  837.56   283.5   838.3   305.7  842.63   330.2  842.62   365.5  840.59
   391.2  843.04   493.1  843.92     603     847   672.2  855.08   680.8  857.77
#Mann= 5 ,-1,0
       0      .1       0     150     .06       0     250      .1       0
   256.8    .045       0   283.5      .1       0
Bank Sta=256.8,283.5
XS Rating Curve= 0 ,0
Exp/Cntr(USF)=0,0
Exp/Cntr=0.3,0.1

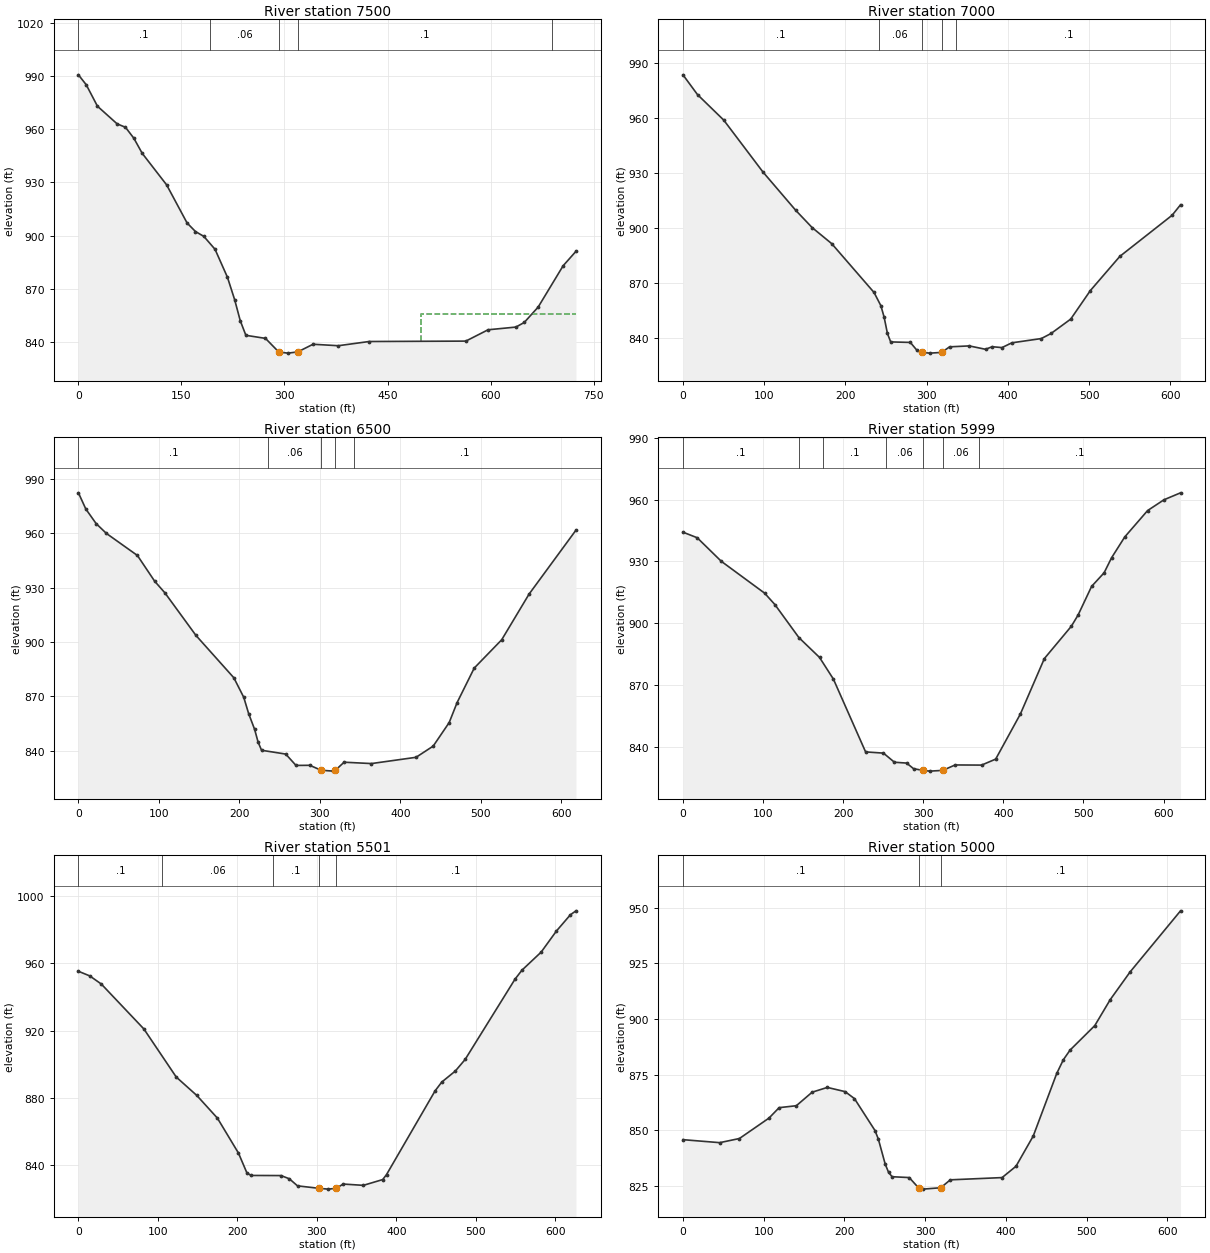
Type RM Length L Ch R = 1 ,7500    ,494.9,500,503.7
XS GIS Cut Line= 6
1662544.90214026360792.0123099981662796.36390768 360742.70597817
  1662894.494945360723.4638906721662968.09387918360709.033801422
1663056.32139301360703.0721991661663258.62862795360734.655662028
#Sta/Elev= 30
       0   990.6    11.4     985    27.7  972.93    56.3     963    68.5  961.06
    80.7  954.89    92.9  946.38   128.4  928.64   158.2  907.17   170.4  902.36
   182.6  899.62   198.9  892.35     217  876.56   227.5  863.91   235.6  852.15
   243.8  843.91   272.3  842.19   291.8834.4829   304.9  833.88   319.2  834.54
   341.6  838.88   378.3  838.05   423.1  840.42     564  840.65   596.4  847.03
   636.9  848.55     649  851.13   669.3   859.8   705.7  883.09   724.4  891.23
#Mann= 5 ,-1,0
       0      .1       0  191.25     .06       0   291.8    .045       0
   319.2      .1       0  689.68     .05       0
#XS Ineff= 2 , 0
                          498.68          855.74
Permanent Ineff=
       F       F
Bank Sta=291.8,319.2
XS Rating Curve= 0 ,0
Exp/Cntr(USF)=0,0
Exp/Cntr=0.3,0.1

Type RM Length L Ch R = 1 ,7000    ,496.9,499.9,501.6
XS GIS Cut Line= 6
1662494.32186083 361183.634558261662587.37843326   361195.015441
1662674.23127793361205.6374670121662748.67666709361214.742435679
1662847.93696725361226.8821751771663102.29177351361257.990708753
#Sta/Elev= 30
       0  983.63    17.9  972.84    50.2  958.93    98.5   930.6   138.8  909.72
     159   900.3   183.1  891.54   235.2  864.91   243.6  857.71   247.6  851.49
   251.7  842.53   255.7  837.93   279.9  837.65   287.9  833.42   293.7832.2133
     304  831.81   318.4  832.19   328.2  835.24   352.4  835.75   372.5   833.9
   380.6  835.31   392.7  834.83   404.8  837.43   441.1  839.76   453.1  842.52
   477.3  850.37   501.5  865.94   537.8   884.6   602.1  907.01   612.5  912.74
#Mann= 5 ,-1,0
       0      .1       0  241.25     .06       0   293.7    .045       0
   318.4     .06       0  336.25      .1       0
Bank Sta=293.7,318.4
XS Rating Curve= 0 ,0
Exp/Cntr(USF)=0,0
Exp/Cntr=0.3,0.1

Type RM Length L Ch R = 1 ,6500    ,498.2,500.9,505
XS GIS Cut Line= 6
1662411.50116034361596.3328798411662501.35334285361630.110043257
1662585.44733475 361662.073890091662656.19719325361689.662745669
1662750.09628367361724.0580180881662990.91830859361811.629693344
#Sta/Elev= 30
       0  982.48     9.2  973.53      22  965.48    34.8  960.03    73.3  947.85
    94.7  933.64   107.5  927.16     146  903.67   193.1  880.24   205.4  869.43
   211.5   860.4   218.9  851.71   223.2   844.7   227.5  840.19   257.5  838.09
   270.3  831.81   287.4  831.88   301.5  829.14   316.8  828.66   319.2829.1221
     330  833.59     364  832.84   419.4   836.3   440.7  842.49   460.6  855.52
   470.4  866.54   491.7  885.63   525.8  901.26   559.8   926.5   618.1  961.87
#Mann= 5 ,-1,0
       0      .1       0  235.96     .06       0   301.5    .045       0
   319.2     .06       0  341.89      .1       0
Bank Sta=301.5,319.2
XS Rating Curve= 0 ,0
Exp/Cntr(USF)=0,0
Exp/Cntr=0.3,0.1

Type RM Length L Ch R = 1 ,5999    ,497.5,498,498
XS GIS Cut Line= 6
1662299.13950843362062.7115402521662472.44690458362123.292455837
1662539.98942043362156.8192916661662623.65296701362211.687620252
1662693.13872042362243.3509427611662872.34800768362290.968629673
#Sta/Elev= 30
       0  944.25    17.8  941.53    47.9  930.08   101.9  914.63   114.8  909.06
   144.8     893   170.5  883.39   187.8  872.87     228  837.49   250.3   836.9
     264  832.47   279.2  832.06   287.9  829.33   299.4  828.53   308.1  828.15
   324.2   828.5   339.8  831.15   372.8  831.08   390.4  833.98   421.2  855.86
   451.2  882.84   484.9  898.55   493.3  903.99   510.2  917.92   525.8  924.52
   535.1  931.81   551.6  941.95   580.1  954.75   600.5  959.98   621.2  963.36
#Mann= 7 ,-1,0
       0      .1       0  145.01     .06       0  175.01      .1       0
  253.67     .06       0   299.4    .045       0   324.2     .06       0
  369.13      .1       0
Bank Sta=299.4,324.2
XS Rating Curve= 0 ,0
Exp/Cntr(USF)=0,0
Exp/Cntr=0.3,0.1

Type RM Length L Ch R = 1 ,5501    ,501.2,501.4,494.1
XS GIS Cut Line= 6
1662248.44768067362464.8111297491662327.02757601362519.473750085
1662529.37231568362689.5633049161662591.41648293362732.281395346
1662678.59019309362761.2016130831662774.95286126362783.143170252
#Sta/Elev= 30
       0  955.27    14.2  952.54    28.8  947.68    82.4  920.92   123.1  892.31
     149  881.34   174.9  867.85   201.4  847.04   212.1  835.15   217.4  833.73
   254.9  833.66   265.4  831.75   275.7  827.53   302.4826.0977   314.3  825.59
   324.4  826.07   333.2  828.61   358.5  827.84   382.9  831.28   387.7  834.25
   448.8  884.09   457.2  889.32   474.2  895.86   486.6  902.77   549.3  950.53
   558.1  955.93   582.2  966.65   601.5  979.25   619.1  988.93   626.1  991.26
#Mann= 5 ,-1,0
       0      .1       0  105.72     .06       0  244.42      .1       0
   302.4    .045       0   324.4      .1       0
Bank Sta=302.4,324.4
XS Rating Curve= 0 ,0
Exp/Cntr(USF)=0,0
Exp/Cntr=0.3,0.1

Type RM Length L Ch R = 1 ,5000    ,503.9,499.8,494.5
XS GIS Cut Line= 6
1662083.47524159363001.6095968341662325.54792017363085.662906423
 1662419.8603956363118.9098871651662489.67718509363146.487587929
 1662575.3125125363169.7319640071662668.94683968363191.645962179
#Sta/Elev= 30
       0  845.75    45.5  844.41    69.9  846.27   106.5  855.45   119.1  860.15
   140.4  861.02     160  867.11   178.8  869.25   200.8  867.36   212.4  864.21
   237.8  849.87     242  845.97   250.5  834.71   254.7  831.01     259  829.09
   280.2  828.71   291.9  824.04   297.1  823.51   319.2 824.135   331.1  827.69
   395.2   828.7   412.4  833.78   433.8   847.4   462.9  875.55   471.1  881.71
   479.4  886.04     510  897.05   529.1  908.71   553.7  921.17   616.2  948.67
#Mann= 3 ,-1,0
       0      .1       0   291.9    .045       0   319.2      .1       0
Bank Sta=291.9,319.2
XS Rating Curve= 0 ,0
Exp/Cntr(USF)=0,0
Exp/Cntr=0.3,0.1

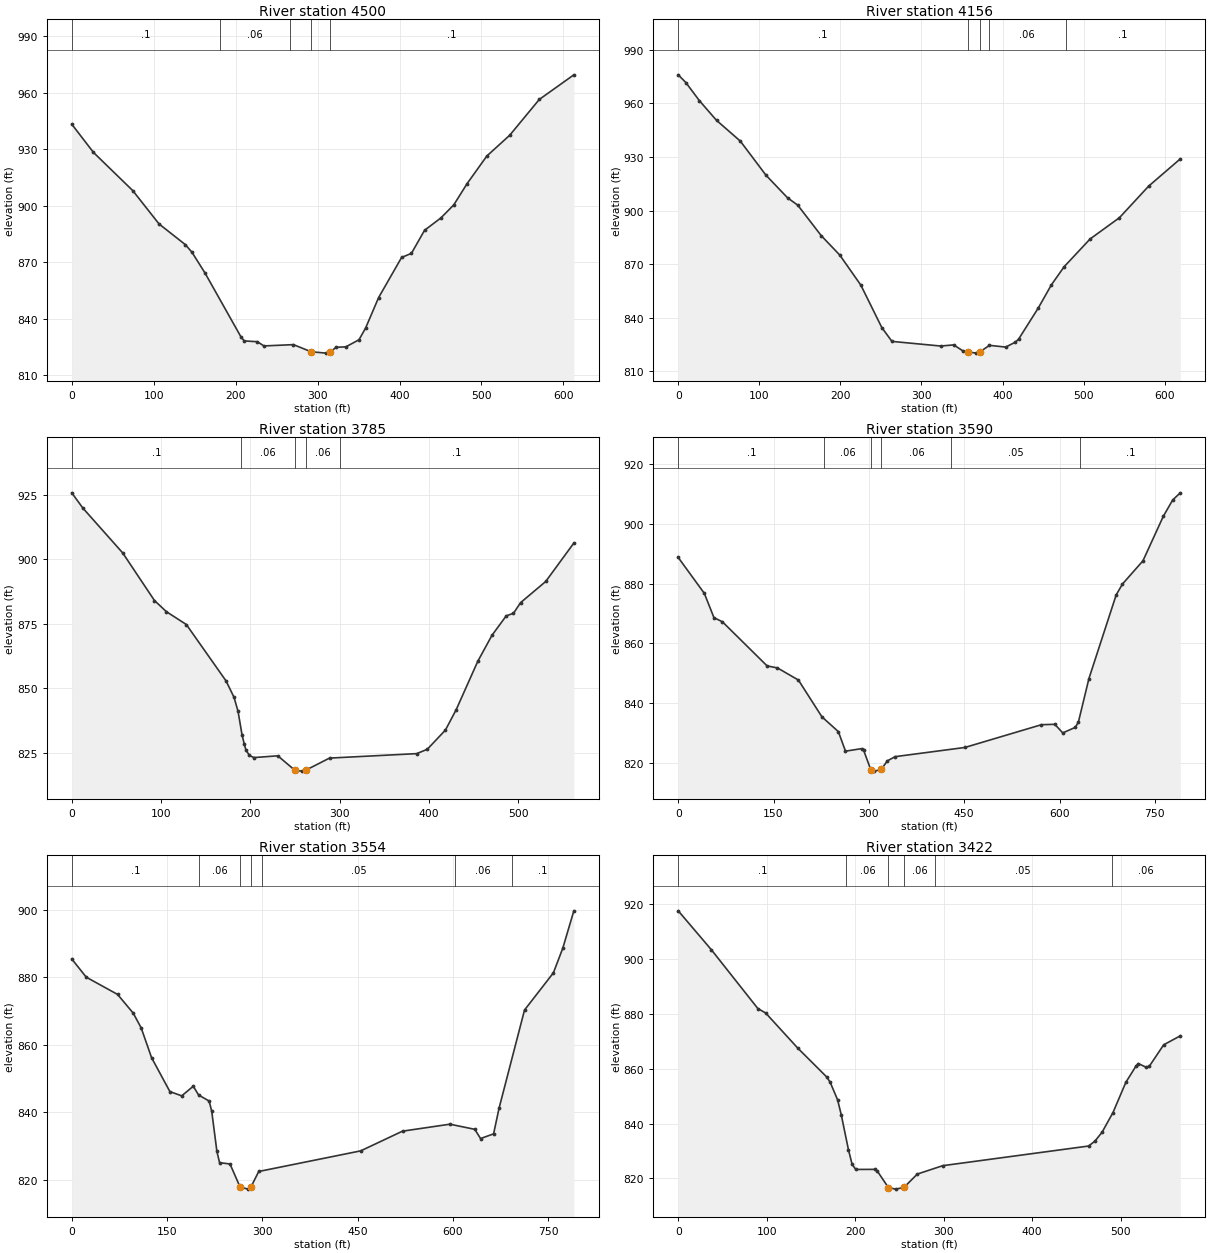
Type RM Length L Ch R = 1 ,4500    ,341.7,344.2,344.2
XS GIS Cut Line= 6
1662061.65835609363597.3082085851662317.89931342363595.154997677
1662417.89583258363594.3141200841662492.90618126363595.256047338
1662580.42930017363597.6408850851662674.24538551363600.317060843
#Sta/Elev= 30
       0  943.36    26.5  928.36    74.5  908.08   106.5  890.41   138.5  879.46
   146.5  875.49   162.5  864.44   206.5  830.43   210.5  828.31   226.5  827.89
   234.5  825.65   270.5  826.34   292.2822.5527   310.5  821.83   315.6822.5205
   322.5  824.92   334.5  825.17   350.5  828.93   358.5  835.08   374.5  851.36
   402.5  872.62   414.5   874.8   430.5  887.03   450.5  893.62   466.2  900.54
   482.5  911.85   506.5  926.46   534.5  937.52   570.5  956.49   612.7  969.57
#Mann= 5 ,-1,0
       0      .1       0  181.25     .06       0  266.25      .1       0
   292.2    .045       0   315.6      .1       0
Bank Sta=292.2,315.6
XS Rating Curve= 0 ,0
Exp/Cntr(USF)=0,0
Exp/Cntr=0.3,0.1

Type RM Length L Ch R = 1 ,4156    ,368.8,371.1,374
XS GIS Cut Line= 6
1661967.20512312363849.6334395611662059.82731321363879.272159805
1662219.54713812363923.7225302211662319.32056061363930.703159308
1662394.21312737363934.7707364761662575.13829046363946.030884554
#Sta/Elev= 30
       0  976.01     9.4  971.69    26.2  961.48    47.2  950.54    76.6  938.88
   108.2  919.81   134.9  907.11   147.4  903.04   176.4  885.94   199.2  875.11
   225.2  858.28   251.1  834.48   263.6  826.73   323.8  824.13   339.8  824.77
   351.8  821.21   356.9820.8192   367.9  820.16   371.9  820.81   383.9  824.52
   403.9  823.54   415.9  826.32   419.9  828.04     444  845.36   460.4  858.48
     476  868.54   508.1  884.12   544.2  895.99   580.2  913.66   619.3  928.95
#Mann= 5 ,-1,0
       0      .1       0   356.9    .045       0   371.9      .1       0
  383.06     .06       0  478.06      .1       0
Bank Sta=356.9,371.9
XS Rating Curve= 0 ,0
Exp/Cntr(USF)=0,0
Exp/Cntr=0.3,0.1

Type RM Length L Ch R = 1 ,3785    ,196.7,195,193.3
XS GIS Cut Line= 3
1661972.96001211364153.3388346161662316.57967736364321.882320611
1662495.57547256  364308.8169341
#Sta/Elev= 30
       0  925.72    12.4  919.82      57  902.45    92.6  883.98     106  879.65
   128.3  874.68   172.8   852.8   181.7  846.46   186.2  841.02   190.6  832.02
   193.1  828.44   195.1  825.96     199  823.92     204  823.11   230.7   823.8
   249.9  818.17   257.5  817.86   261.8  818.19   288.6  822.91   386.3  824.64
   398.1  826.33   418.4  833.77   430.4  841.63   454.6   860.4   470.5  870.49
   486.5  878.04   494.6  879.03   502.6  883.17   530.7  891.36   562.2  906.26
#Mann= 5 ,-1,0
       0      .1       0     190     .06       0   249.9    .045       0
   261.8     .06       0     300      .1       0
Bank Sta=249.9,261.8
XS Rating Curve= 0 ,0
Exp/Cntr(USF)=0,0
Exp/Cntr=0.3,0.1

Type RM Length L Ch R = 1 ,3590    ,35.5,35.4,35.5
XS GIS Cut Line= 3
1661824.18630142364372.7322008141662400.51501753364510.644613989
1662516.65178651364350.956556629
#Sta/Elev= 30
       0  888.71    41.1  876.71    56.2  868.62    69.5  867.24   139.8  852.52
   156.2  851.82   189.1  847.79   226.1  835.51     252  830.56   263.2  824.04
   288.5  824.89   291.9  824.27   302.9   817.9   308.4  817.38   319.4817.9274
     329   820.8   341.3  822.21   451.1  825.28   571.6  832.88   592.6  833.01
   605.1  830.14   624.9  831.99   629.8  833.82   646.3  848.29   689.2  876.22
   699.1  879.85   731.3  887.59   763.4  902.48   778.2  907.93   790.1  910.29
#Mann= 6 ,-1,0
       0      .1       0     230     .06       0   302.9    .045       0
   319.4     .06       0     430     .05       0   632.6      .1       0
Bank Sta=302.9,319.4
XS Rating Curve= 0 ,0
Exp/Cntr(USF)=0,0
Exp/Cntr=0.3,0.1

Type RM Length L Ch R = 1 ,3554    ,131.6,131.8,131.4
XS GIS Cut Line= 3
1661853.94634847364416.2834891851662430.27506458 364554.19590236
1662546.41183357   364394.507845
#Sta/Elev= 30
       0   885.4    22.8  880.01    72.1  874.91    96.8  869.35   109.2  865.02
   125.6  856.19   154.4  846.17     173   844.9   191.2  847.75   199.6  845.15
   216.1  843.38   220.2  840.41   228.4  828.46   232.6  825.14     249  824.75
   264.9  817.91   277.8  817.31   281.9   817.9   294.2  822.53   454.7  828.63
   520.5  834.46   595.1  836.52   634.2     835   643.3  832.27   663.8  833.66
   672.4  841.24   712.5   870.3   757.9  881.29   772.7  888.58   790.1  899.64
#Mann= 7 ,-1,0
       0      .1       0     200     .06       0   264.9    .045       0
   281.9     .06       0     300     .05       0   602.6     .06       0
   692.6      .1       0
Bank Sta=264.9,281.9
XS Rating Curve= 0 ,0
Exp/Cntr(USF)=0,0
Exp/Cntr=0.3,0.1

Type RM Length L Ch R = 1 ,3422    ,419.8,421.2,422.8
XS GIS Cut Line= 2
1661856.18438322364555.9224083191662410.45242295364677.730015344
#Sta/Elev= 30
       0  917.51    37.4  903.35      90  881.91    98.8   880.3   135.1   867.5
   167.8  856.99   171.7  855.08   180.1  848.67   184.2   843.3   192.4  830.47
   196.5   825.2   200.6  823.29   222.1  823.32   225.2   822.6   237.5  816.71
   245.6  816.12   255.1816.7289   270.2   821.6   298.9  824.66   463.8  831.82
   470.9  833.58   479.1  836.87   491.4  844.02     506  855.07   517.5     861
   520.1  861.86   528.2  860.62   532.3   860.8   548.7   868.7   567.5  871.97
#Mann= 6 ,-1,0
       0      .1       0     190     .06       0   237.5    .045       0
   255.1     .06       0     290     .05       0     490     .06       0
Bank Sta=237.5,255.1
XS Rating Curve= 0 ,0
Exp/Cntr(USF)=0,0
Exp/Cntr=0.3,0.1

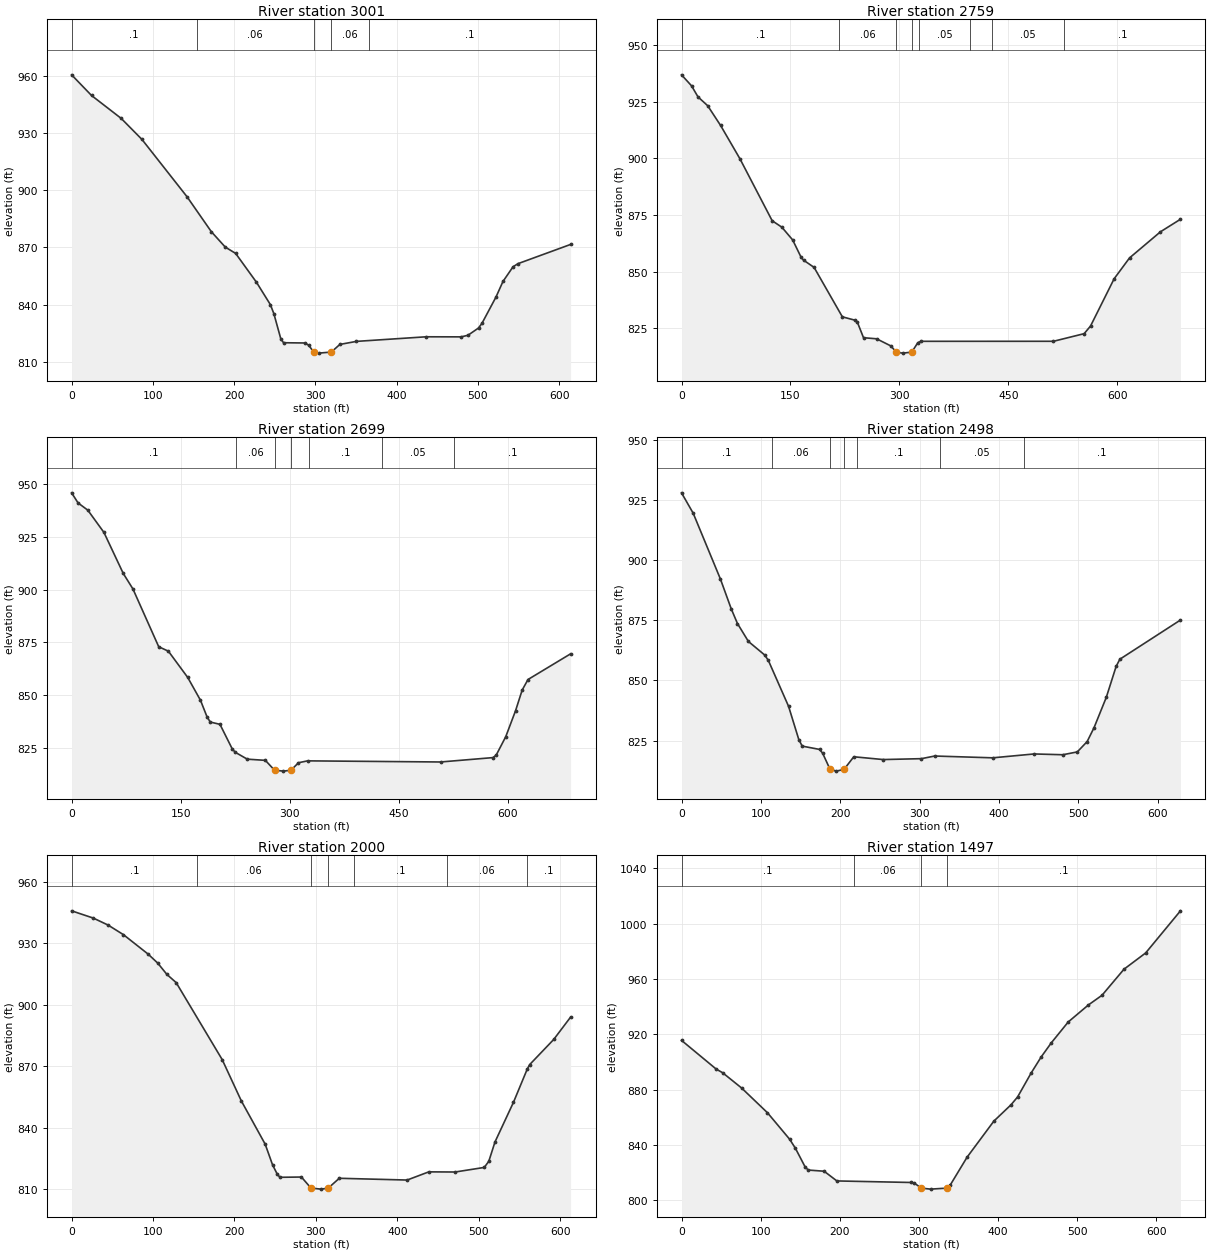
Type RM Length L Ch R = 1 ,3001    ,242.9,242.2,240.9
XS GIS Cut Line= 6
1661698.97174551  364902.14385351661938.95945451364991.797217503
1662032.43236467365027.4129599181662103.42106783365052.216059923
1662185.51768842365084.1507073341662273.16843176365119.650964424
#Sta/Elev= 30
       0  960.57    24.5  949.74      61  937.72    86.6  926.67   142.1  896.59
     172  878.27   189.1  870.22   201.9  866.89   227.5  851.77   244.6  840.06
   248.9  835.33   257.4  822.21   260.8  820.04   287.4  819.91   291.7  818.74
     298815.2056   304.1  814.59   319.6  815.15   330.2  819.16   350.6  820.75
   436.4  823.16   479.4  823.12   487.8  823.95   500.8  827.76   505.1  830.25
   522.3     844   530.9  852.18   543.3  859.88   549.4  861.52   614.1   871.6
#Mann= 5 ,-1,0
       0      .1       0  153.71     .06       0     298    .045       0
   319.6     .06       0  366.22      .1       0
Bank Sta=298,319.6
XS Rating Curve= 0 ,0
Exp/Cntr(USF)=0,0
Exp/Cntr=0.3,0.1

Type RM Length L Ch R = 1 ,2759    ,59.8,59.7,59.7
XS GIS Cut Line= 4
1661647.63361484  365308.22986391661834.02596013365218.618159433
1662156.62809621  365308.22986391662289.25341882365249.086138952
#Sta/Elev= 30
       0  936.82    13.8  931.97    22.7  927.09      36  923.21    53.8  914.49
    80.4  899.82   124.8  872.49   138.1  869.65     153  864.03   164.7  856.33
     168  855.11   182.5  851.92   221.4  830.13   239.3   828.6   242.2  827.65
   250.5  820.93   268.6  820.44   287.9  817.34   295.9814.5476   304.3  814.13
   316.9  814.56   325.2   818.7   329.4  819.34     512  819.35   554.2  822.71
     563  826.07   595.5  846.92   616.7  856.11   659.3  867.63   686.8  873.15
#Mann= 8 ,-1,0
       0      .1       0  216.81     .06       0   295.9    .045       0
   316.9     .06       0  326.81     .05       0  396.81      .1       0
  426.81     .05       0  526.81      .1       0
Bank Sta=295.9,316.9
XS Rating Curve= 0 ,0
Exp/Cntr(USF)=0,0
Exp/Cntr=0.3,0.1

Type RM Length L Ch R = 1 ,2699    ,208.2,201.5,195.2
XS GIS Cut Line= 4
1661644.04914666365369.1658229371661830.44149195365279.554118471
1662153.04362803365369.1658229371662285.66895064365310.022097989
#Sta/Elev= 30
       0   945.8     8.9  941.01    22.3  937.59    44.5  927.06    71.1  907.63
    84.4  900.31   119.9  872.95   133.2  870.85   159.8  858.43   177.4  847.61
   186.5  839.67   190.9  837.31   204.2  836.23     221  824.66   225.2  823.01
   241.8  819.74   266.7  819.18   279.3814.5254   291.6  814.08   301.9814.5048
   312.3  818.05   324.8  818.94   507.9  818.41     580  820.48   584.4  821.64
   597.6  830.39   611.1  842.69   620.2  852.45   628.2  857.44   686.8  869.59
#Mann= 7 ,-1,0
       0      .1       0  226.81     .06       0   279.3    .045       0
   301.9     .06       0  326.81      .1       0  426.81     .05       0
  526.81      .1       0
Bank Sta=279.3,301.9
XS Rating Curve= 0 ,0
Exp/Cntr(USF)=0,0
Exp/Cntr=0.3,0.1

Type RM Length L Ch R = 1 ,2498    ,505,497.8,492.3
XS GIS Cut Line= 6
1661738.44056568365568.0261904161661977.19074434365474.953541921
1662070.36181785365438.633732663 1662139.4689631365409.148555414
1662222.48192044365371.3051271751662321.48861218 365332.95284167
#Sta/Elev= 30
       0  927.98    14.7  919.51      49  892.16    62.7  879.71    70.5  873.64
    84.3  866.19   104.8  860.56   109.4  858.32   134.9  839.23   147.8  825.42
   152.1  822.68   173.9  821.31   177.8  819.76   187.2813.0188     195  812.28
   204.8     813   217.1  818.25   254.2  817.09   302.3  817.46   319.1  818.56
   392.2  817.81   444.4  819.42   480.5  819.09   498.8  820.27   511.2  824.57
   519.9  830.35   535.3  842.93   547.7   855.8   552.4   858.8   628.8   875.1
#Mann= 7 ,-1,0
       0      .1       0  113.75     .06       0   187.2    .045       0
   204.8     .06       0  221.25      .1       0  326.25     .05       0
  431.38      .1       0
Bank Sta=187.2,204.8
XS Rating Curve= 0 ,0
Exp/Cntr(USF)=0,0
Exp/Cntr=0.3,0.1

Type RM Length L Ch R = 1 ,2000    ,477.1,502.9,515.9
XS GIS Cut Line= 6
1662161.35172626366058.5273675021662211.10917267365978.866437584
1662288.65790209365836.0629174261662336.38024759365748.184812337
1662372.17151459365682.2768076661662458.66707651365522.997598678
#Sta/Elev= 30
       0  945.76    26.7  942.21    44.8  938.81    63.7  934.12    93.9  924.67
   105.7  920.29     117  914.75   128.4  910.75   184.9   873.2   208.5  852.98
   237.7  831.95   246.8  821.82   252.7  817.19   255.9   815.8   282.2  815.93
     294  810.52   306.4  810.03   315.1  810.52   328.7  815.32     412  814.46
   438.6  818.45     471  818.38   506.7  820.61   512.3  823.61   519.9  833.04
   542.6  852.39   559.5  868.57   562.5  870.77     592  883.02   612.7  893.91
#Mann= 7 ,-1,0
       0      .1       0  153.92     .06       0     294    .045       0
   315.1     .06       0  346.42      .1       0  461.42     .06       0
  558.92      .1       0
Bank Sta=294,315.1
XS Rating Curve= 0 ,0
Exp/Cntr(USF)=0,0
Exp/Cntr=0.3,0.1

Type RM Length L Ch R = 1 ,1497    ,494.8,497.1,494.7
XS GIS Cut Line= 6
1662220.22037493366135.5278696721662328.84647001 366132.86678575
1662493.42750567366151.8674039241662588.97094975366181.855532929
1662741.16388685366238.8114557561662829.51705658 366270.21821709
#Sta/Elev= 30
       0  915.72    43.9  894.94    51.9  892.36    75.9  881.32   108.7  863.38
   136.8  844.18   144.1  837.61   156.2  824.31   160.2  821.98   180.3  821.13
   196.4  814.11   289.7     813   293.9   812.7   303.3   808.9   314.9  808.19
   335.1808.9043     340  811.39     361  831.25   394.9  857.36   416.6  869.16
   424.9  874.83     442  892.11   454.8  903.82   467.6  914.01   488.9  929.02
   514.5  941.36   531.6  948.31   559.4  967.16   586.8  978.91   630.8 1009.36
#Mann= 4 ,-1,0
       0      .1       0  218.06     .06       0   303.3    .045       0
   335.1      .1       0
Bank Sta=303.3,335.1
XS Rating Curve= 0 ,0
Exp/Cntr(USF)=0,0
Exp/Cntr=0.3,0.1

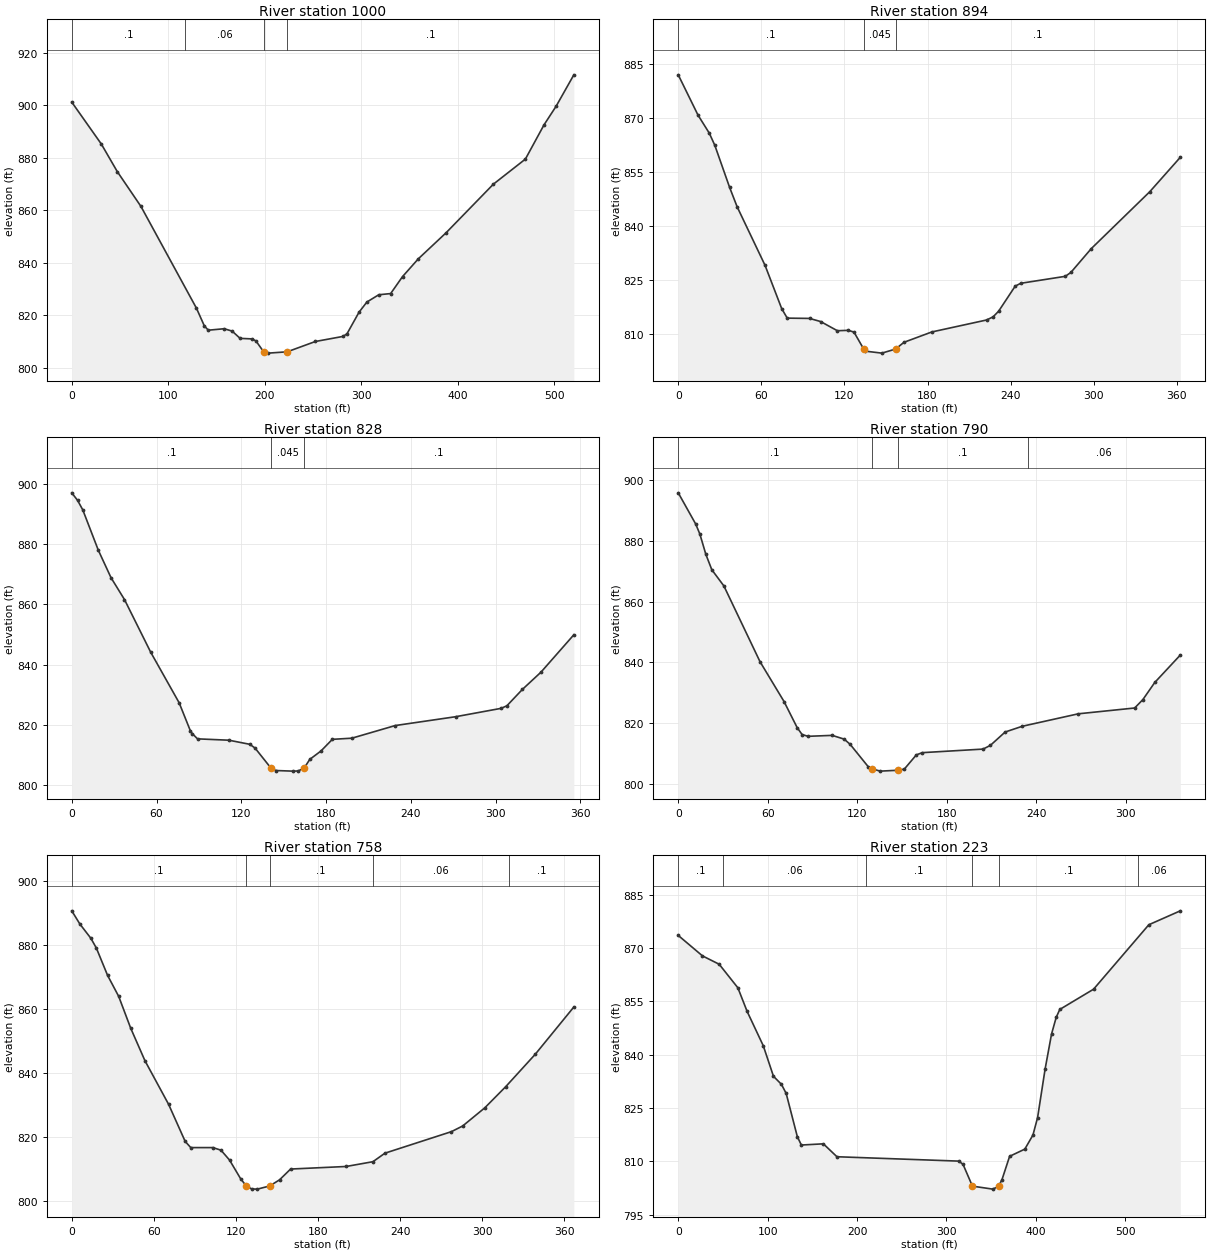
Type RM Length L Ch R = 1 ,1000    ,110.7,106.6,103.3
XS GIS Cut Line= 6
1662130.29798259366561.9108751711662288.47614393366598.792691171
1662385.94871801366621.4087876681662459.10244308366638.527519837
1662544.70496218366657.6642925891662638.70838308  366670.5418915
#Sta/Elev= 30
       0   901.1    30.6  885.16    47.1  874.68    71.7  861.37   129.2  822.62
   137.4  815.85   141.5  814.25   157.9  814.81   166.2   813.9   174.4  811.14
   186.7  810.94   190.8  810.17   198.7806.0914   203.6  805.52   223.2  806.02
   252.4  809.95   281.1  811.89   285.2  812.91   297.6  821.09   305.8  824.99
   318.1  827.75   330.4   828.2   342.7  834.66   359.1  841.45   387.8  851.34
   436.8  869.85     470  879.41   489.3  892.45   501.9  899.58   520.2   911.5
#Mann= 4 ,-1,0
       0      .1       0  117.46     .06       0   198.7    .045       0
   223.2      .1       0
Bank Sta=198.7,223.2
XS Rating Curve= 0 ,0
Exp/Cntr(USF)=0,0
Exp/Cntr=0.3,0.1

Type RM Length L Ch R = 1 ,894     ,65.7,65.4,65.8
XS GIS Cut Line= 4
1662185.86737647366730.2098844591662253.92224123366722.246017308
1662476.18653356366703.4223313121662539.89747077366672.290850627
#Sta/Elev= 30
       0  882.08    14.3  870.84    22.4  865.84    26.4  862.45    37.1  850.71
    42.5  845.33    62.7  828.98    74.7  816.94    78.7  814.29    94.8  814.21
   102.8  813.34   114.9  810.78   122.9  810.89   126.9  810.39   133.8805.7538
   134.9   805.1     147  804.54   156.9805.6712     163  807.56   183.1  810.44
   222.6  813.77   227.3  814.64   231.3  816.21   243.3  823.21   247.3     824
   279.5  825.94   283.5  827.03   298.2  833.65   340.5  849.53   362.5   859.1
#Mann= 3 ,-1,0
       0      .1       0   133.8    .045       0   156.9      .1       0
Bank Sta=133.8,156.9
XS Rating Curve= 0 ,0
Exp/Cntr(USF)=0,0
Exp/Cntr=0.3,0.1

Type RM Length L Ch R = 1 ,828     ,38.5,38.1,38
XS GIS Cut Line= 4
1662192.38326778366793.1968337521662384.24006735366776.545111526
1662433.47124611 366735.27779992 1662531.2096157 366722.97000523
#Sta/Elev= 30
       0  897.04     4.1  894.54     7.8  891.37    18.8  877.96    27.8  868.83
    37.3  861.59    55.9  844.06      76  827.29      84  817.91    85.3  817.06
      89  815.32   111.2  814.87     126  813.51   129.7  812.26   140.8805.7042
   144.3   804.8   156.3   804.6   160.3  804.65   164.6805.7188   168.4  808.49
   176.4  811.31   184.4  815.16   198.2  815.54   228.9  819.74   271.6  822.67
   303.8  825.45   307.9   826.3   318.9  831.75     332  837.45   355.3  849.89
#Mann= 3 ,-1,0
       0      .1       0   140.8    .045       0   164.6      .1       0
Bank Sta=140.8,164.6
XS Rating Curve= 0 ,0
Exp/Cntr(USF)=0,0
Exp/Cntr=0.3,0.1

Type RM Length L Ch R = 1 ,790     ,32.6,32.3,31.9
XS GIS Cut Line= 4
1662209.75897793366835.1881332811662412.47559634366809.848555979
1662467.49867848366760.6173772221662524.69372439366749.033570455
#Sta/Elev= 30
       0  895.66    11.7  885.43    14.5  882.13    18.5  875.49    22.5  870.43
    30.6  865.11    54.8  840.27    70.9   827.2    79.7  818.64      83  816.37
      87  815.78   103.2  816.09   111.2  814.86   115.2  813.16   127.3  805.83
   129.8805.1044   135.4  804.36   147.5  804.65   151.5  805.01   159.6   809.7
   163.6  810.42   204.3  811.59   209.2  812.81   219.1  817.19   230.6  819.08
   268.2  823.17   305.9  825.07   311.4  827.82   319.4  833.46   336.5  842.44
#Mann= 4 ,-1,0
       0      .1       0   129.8    .045       0   147.5      .1       0
  234.29     .06       0
Bank Sta=129.8,147.5
XS Rating Curve= 0 ,0
Exp/Cntr(USF)=0,0
Exp/Cntr=0.3,0.1

Type RM Length L Ch R = 1 ,758     ,520,534.6,542.2
XS GIS Cut Line= 2
1662218.31845633366872.4218459841662580.34974238366811.485886947
#Sta/Elev= 30
       0  890.55     5.9  886.45      14  881.97      18  878.92    26.2  870.41
    34.3  863.89    43.1  853.95    53.5  843.83    70.8  830.23    82.9  818.68
      87  816.74   103.2  816.74   109.1  815.93   115.4  812.83   123.5     807
   127.6  804.78   131.6  803.84   135.7  803.79   144.7 804.773   151.9  806.68
     160  810.05   200.6  810.85   220.2  812.34     229     815   277.6  821.71
   285.8  823.47     302  829.14   317.4  835.78   338.9  845.84   367.1  860.57
#Mann= 5 ,-1,0
       0      .1       0   127.6    .045       0   144.7      .1       0
     220     .06       0     320      .1       0
Bank Sta=127.6,144.7
XS Rating Curve= 0 ,0
Exp/Cntr(USF)=0,0
Exp/Cntr=0.3,0.1

Type RM Length L Ch R = 1 ,223     ,,,
XS GIS Cut Line= 3
1662035.51057922367107.204511686  1662392.165163367404.715370515
1662479.98463338367363.493986461
#Sta/Elev= 30
       0  873.51    27.1  867.76    45.8  865.41    66.7  858.79      77  852.18
    95.1  842.51   106.5  833.93   115.4  831.67   120.7  829.12   133.2  816.95
   137.7  814.61   162.3  814.95   177.5  811.32   313.8  810.09   318.5  809.19
     329  803.06   351.8  802.22   358.2  802.98   362.1  804.91   370.6  811.44
   387.6  813.46   396.7  817.42   401.9  822.34   410.3  835.97   417.5  845.81
   422.7  850.48   426.7  852.71   464.5   858.4   526.3  876.51   561.5  880.42
#Mann= 6 ,-1,0
       0      .1       0      50     .06       0     210      .1       0
     329    .045       0   358.2      .1       0  514.45     .06       0
Bank Sta=329,358.2
XS Rating Curve= 0 ,0
Exp/Cntr(USF)=0,0
Exp/Cntr=0.3,0.1
LCMann Table=0

Chan Stop Cuts=-1
Use User Specified Reach Order=0
Composite Channel Slope=5